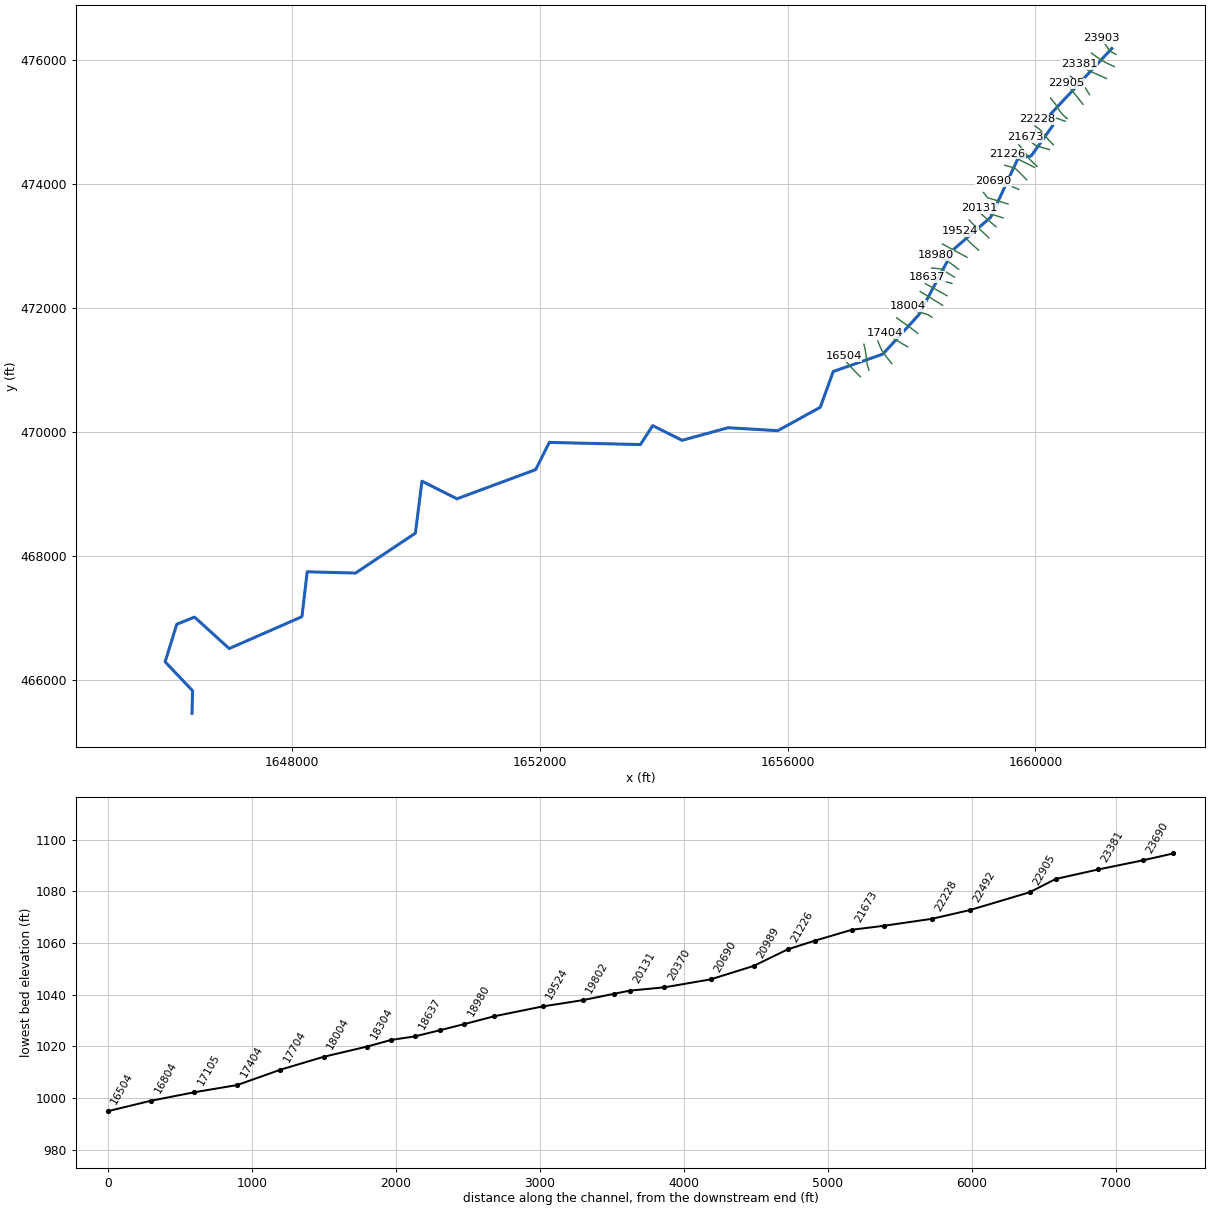
--- MagtyRn.prj (project) ---

Proj Title=MagtyRn
Current Plan=p01
Default Exp/Contr=0,0
English Units
Geom File=g01
Flow File=f01
Plan File=p01
BEGIN DESCRIPTION:
---------- MODELED AS PART OF WVEM CTP PROGRAM, 2025----------
Stream Name: Maggoty Run
Flood Zone: AFH
Marshall County, WV
HEC-RAS Version: RAS 6.6
Vertical Datum: NAVD88
Projection: NAD 1983 StatePlane West Virginia N FIPS 4701 (US Feet)
Terrain: 1-meter West Virginia FEMA R3 South Central (collected 2018-2019)
Land Use: 2024 NLCD
Hydrologic Method:
Duda et al., "Estimation of magnitude and frequency of floods for rural, unregulated streams in and near Virginia and West Virginia." September 8, 2025.
Additional Model Notes:
None
END DESCRIPTION:
DSS Export Rating Curves= 0
DSS Export Rating Curve Sorted= 0
DSS Export Volume Flow Curves= 0
DXF OffsetX= 0
DXF OffsetY= 0
DXF ScaleX= 0
DXF ScaleY= 0

--- MagtyRn.p01 (plan) ---

Plan Title=Floodplain
Program Version=6.60
Short Identifier=Floodplain
Geom File=g01
Flow File=f01
Subcritical Flow
K Sum by GR= 0
Std Step Tol= 0.01
Critical Tol= 0.01
Num of Std Step Trials= 20
Max Error Tol= 0.3
Flow Tol Ratio= 0.001
Split Flow NTrial= 30
Split Flow Tol= 0.02
Split Flow Ratio= 0.02
Log Output Level= 0
Friction Slope Method= 1
Unsteady Friction Slope Method= 2
Unsteady Bridges Friction Slope Method= 1
Parabolic Critical Depth
Global Vel Dist= 0 , 0 , 0
Global Log Level= 0
CheckData=False
Encroach Param=-1 ,0,0, 0
Flow Ratio Tolerance=0.1
Flow Ratio Min Ratio=0.5
Flow Ratio Max Ratio=4
Flow Ratio Max Iterations= 10
Mapping Interval=1HOUR
Computation Time Step Use Courant=        0
Computation Time Step Use Time Series=    0
Computation Time Step Count To Double=0
Computation Time Step Max Doubling=0
Computation Time Step Max Halving=0
Computation Time Step Residence Courant=0
Run HTab= 0
Run UNet= 0
Run Sediment= 0
Run PostProcess= 0
Run WQNet= 0
Run RASMapper=-1
UNET Theta= 0
UNET Theta Warmup= 0
UNET ZTol= 0
UNET ZSATol= 0
UNET MxIter= 0
UNET Max Iter WO Improvement= 0
UNET MaxInSteps= 0
UNET DtIC= 0
UNET DtMin= 0
UNET MaxCRTS= 0
UNET WFStab= 0
UNET SFStab= 0
UNET WFX= 1
UNET SFX= 1
UNET Gravity=32.17405
UNET 1D Methodology=Finite Difference
UNET DSS MLevel= 1
UNET Pardiso=0
UNET DZMax Abort= 0
UNET Use Existing IB Tables= 0
UNET Froude Reduction=False
UNET Froude Limit= 0
UNET Froude Power= 0
UNET D1 Cores= 0
UNET WindReference=Eulerian
UNET WindDragFormulation=Hsu (1988)
UNET D2 Coriolis=0
UNET D2 Cores= 0
UNET D2 Theta= 1
UNET D2 Theta Warmup= 1
UNET D2 Z Tol= 0.01
UNET D2 Volume Tol= 0.01
UNET D2 Max Iterations= 20
UNET D2 Advanced Convergence=0
UNET D2 WS Max Tol=0.15
UNET D2 WS RMS Tol=0.002
UNET D2 WS Stall Tol=1
UNET D2 Equation= 0
UNET D2 RampUpFraction=0.1
UNET D2 TimeSlices= 1
UNET D2 Turbulence Formulation=Non-Conservative (original)
UNET D2 Eddy Viscosity=0.3
UNET D2 Transverse Eddy Viscosity=0.1
UNET D2 Smagorinsky Mixing=0
UNET D2 BCVolumeCheck=0
UNET D2 Cores=0
UNET D2 SolverType=PARDISO (Direct)
UNET D2 Minimum Iterations= 3
UNET D2 Maximum Iterations= 30
UNET D2 Restart Number= 10
UNET D2 Relaxation Coeff=1.3
UNET D2 SOR Precondition Iterations= 10
UNET D2 ILUT Maximum Fill= 8
UNET D2 ILUT Tolerance=1E-08
UNET D2 Convergence Tolerance=0.00001
PS Theta= 1
PS WS Tol= 0.01
PS Volume Tol= 0.01
PS Max Iterations= 20
PS Equation= 0
PS Advance Time Step=-1
PS Target Courant=0.9
PS Time Slices= 1
PS Iterate With 2D=0
PS Project Initial WSE from DS=-1
PS Ramp Up Initial WSE from US=-1
PS Cores=0
UNET D1D2 MaxIter= 0
UNET D1D2 ZTol=0.01
UNET D1D2 QTol=0.1
UNET D1D2 MinQTol=1
Write IC File= 0
Write IC File at Fixed DateTime=0
Write IC File at Sim End=0
Echo Input=False
Echo Parameters=False
Echo Output=False
Write Detailed= 0
HDF Write Warmup=0
HDF Write Time Slices=0
HDF Flush=0
HDF Compression= 1
HDF Chunk Size= 1
HDF Spatial Parts= 1
HDF Use Max Rows=0
HDF Fixed Rows= 1
Calibration Method= 0
Calibration Iterations= 20
Calibration Max Change=0.05
Calibration Tolerance=0.2
Calibration Maximum=1.5
Calibration Minimum=0.5
Calibration Optimization Method= 1
WQ AD Non Conservative
WQ ULTIMATE=-1
WQ Max Comp Step=1HOUR
WQ Output Interval=15MIN
WQ Output Selected Increments= 0
WQ Create Restart=0
WQ Fixed Restart=0
WQ System Summary=0
WQ Write To DSS=0
Sorting and Armoring Iterations= 10
XS Update Threshold= 0.02
Bed Roughness Predictor= 0
Processes Affected by Predictor=Sediment Only
Hydraulics Update Threshold= 0.02
Energy Slope Method= 1
Volume Change Method= 1
Sediment Retention Method= 0
Sediment TS Multiplier= 1
Warm Up Method= 0
XS Weighting Method= 0
Number of US Weighted Cross Sections= 1
Number of DS Weighted Cross Sections= 1
Upstream XS Weight=0
Main XS Weight=1
Downstream XS Weight=0
Number of DS XS's Weighted with US Boundary= 1
Upstream Boundary Weight= 1
Weight of XSs Associated with US Boundary= 0
Number of US XS's Weighted with DS Boundary= 1
Downstream Boundary Weight= 0.5
Weight of XSs Associated with DS Boundary= 0.5
Percentile Method= 0
Sediment Output Level= 3
Mass or Volume Output= 0
Output Increment Type= 1
Profile and TS Output Increment= 1
Transport Output Increment 1
XS Output Flag= 0
XS Output Increment= 10
Read HDF5 Sediment Hotstart= 0
Sediment Hotstart Type= 0
Write Gradation File= 0
Read Gradation Hotstart= 0
Write HDF5 File= 1
Write Binary Output= 1
Write DSS Sediment File= 0
DSS Sediment Output Type= 1
SV Curve= 0
Specific Gage Flag= 0
Subcell Erosion Methods= 0
Subcell Deposition Methods= 0
Advection Scheme= 1
Matrix Solver= 0
Implicit Weighting Factor= 1
Maximum Outer Loop Convergence Iterations= 5
Convergence Maximum Absolute= 0.001
Convergence RMSE= 0.0001
Grain Fractions Max Abs Error= 0.001
Max Subgrid Regions= 1
Max Subgrid Length Scale= 3.402823E+38
Initial Layer Thickness= 3
Min Layer Thickness= 0.1
Max Layer Thickness= 6
Number of Layers= 5

--- MagtyRn.f01 (steady flow) ---

Flow Title=Flow
Program Version=6.60
Number of Profiles= 1
Profile Names=P100yr
River Rch & RM=MagtyRn,Main,23903
     880
River Rch & RM=MagtyRn,Main,20018
    1050
River Rch & RM=MagtyRn,Main,16504
    1230
River Rch & RM=MagtyRn,Main,10818
    1940
River Rch & RM=MagtyRn,Main,8713
    2240
River Rch & RM=MagtyRn,Main,7800
    2490
Boundary for River Rch & Prof#=MagtyRn,Main            , 1
Up Type= 0
Dn Type= 3
Dn Slope=0.014991
DSS Import GetInterval= 0
DSS Import GetPeak= 0
DSS Import FillOption= 0

--- MagtyRn.g01 (geometry) ---

Geom Title=Geometry
Program Version=6.60

River Reach=MagtyRn         ,Main
Reach XY= 30
1661234.77923106476189.5914368051660203.96423681 475084.72466898
1660286.02968948474951.1179808081659932.74758764474454.220680639
1659723.58035505 474420.693844811659278.76731176473463.066903447
1658682.96432605 472948.436618731658119.84635781471890.890177399
1657538.59423947471255.2648082231656737.34420155470974.183349401
1656527.87513231470396.5995308161655841.67834197470018.730535895
1655039.09923847 470066.653340311654297.32545955469863.218379721
1653822.16860147470100.1670528051653623.97017898469794.498700887
1652153.53053455 469829.622974471651932.22225013 469389.99983798
1650662.22216547468918.8889035581650096.81056663469203.171471477
1649990.31471664468363.9467719791649024.71100481467719.822075978
1648243.91105722467740.4444100561648158.88891755467015.555439889
1646984.53332664466500.9777288881646424.44455181467008.888786554
 1646137.7778023  466893.33324341645949.99996264466286.800007641
 1646393.5548498 465819.336047561646383.34259988465454.383037314

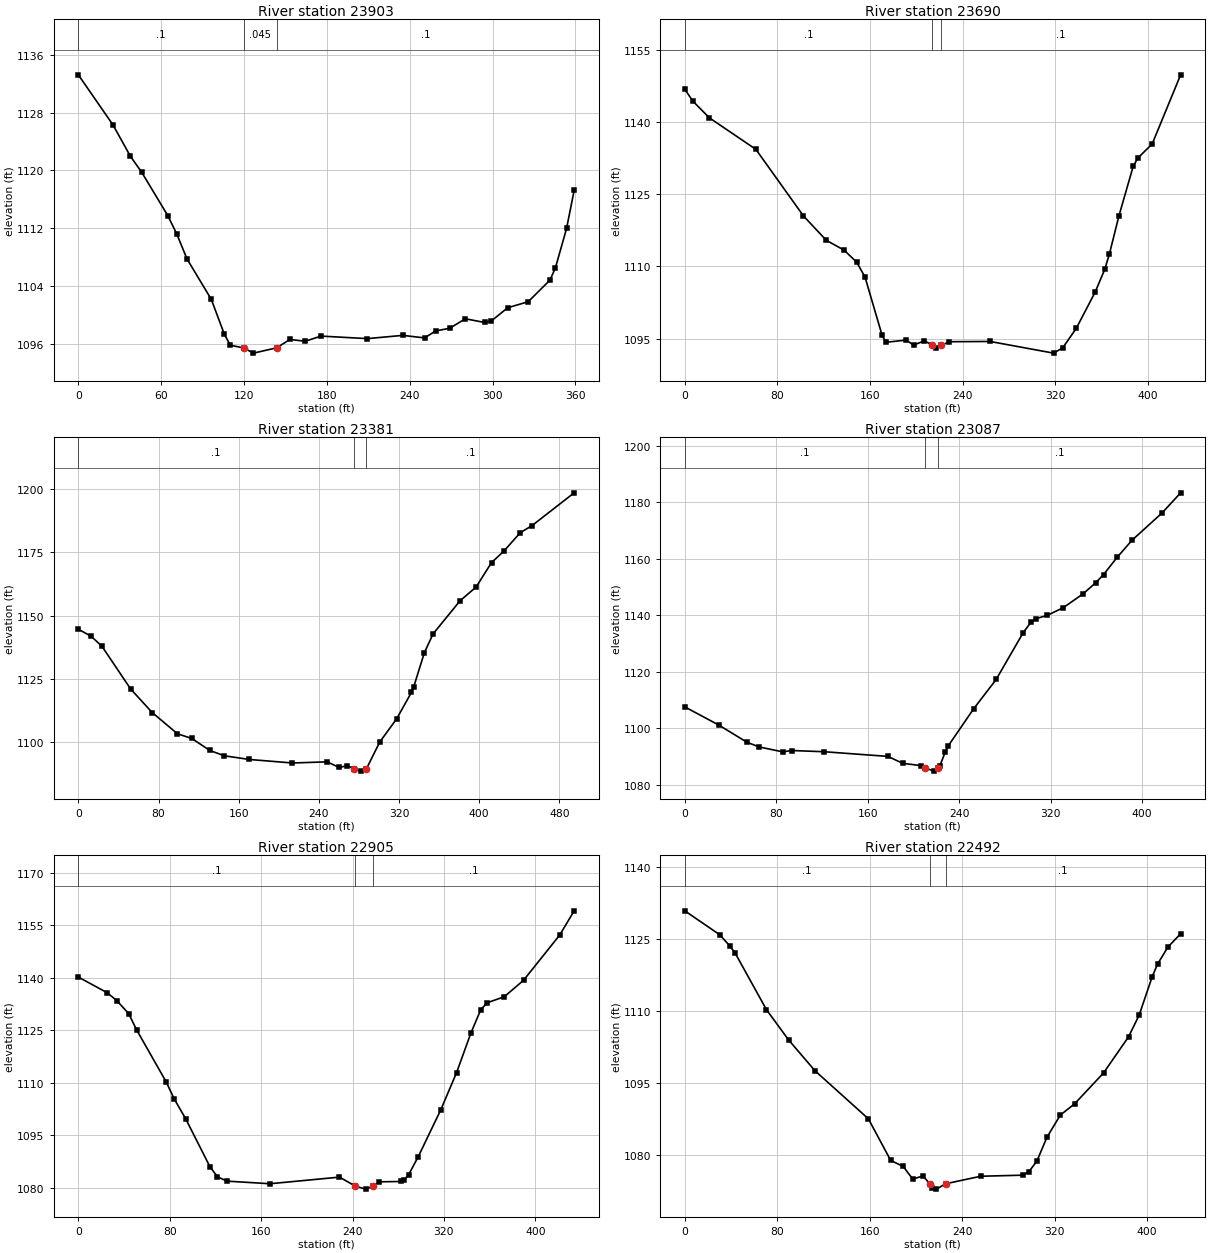
Type RM Length L Ch R = 1 ,23903   ,205.3,213.1,214.1
XS GIS Cut Line= 4
1661302.00422849476094.377207772  1661211.699017476142.970012049
1661180.30720539476182.5322951781661065.73427186476353.752881102
#Sta/Elev= 30
       0 1133.25    25.1 1126.31    37.7 1121.97    45.9 1119.75    64.8 1113.74
    71.3  1111.2    78.7 1107.74    96.3 1102.14   105.8 1097.28   110.1 1095.79
   119.9  1095.4   126.8 1094.69   143.6 1095.42   153.2 1096.58   164.4 1096.34
   175.8 1097.05   209.3  1096.7     235 1097.15   250.8  1096.8   258.7 1097.76
     269 1098.14   280.3 1099.45   294.2 1098.94   299.2 1099.16     311 1100.98
   325.8 1101.81   341.6 1104.81   345.5 1106.49   353.6 1111.96   359.1 1117.24
#Mann= 3, -1 ,  0
       0     0.1       0   119.9   0.045       0   143.6     0.1       0
Bank Sta=119.9,143.6
XS Rating Curve= 0 ,0
Exp/Cntr(USF)=0,0
Exp/Cntr=0.3,0.1

Type RM Length L Ch R = 1 ,23690   ,303.6,309.7,304.2
XS GIS Cut Line= 6
1661274.83250192475896.7519163341661194.13876568475935.725591674
1661125.50898167475967.6782836771661041.09248383476021.302848339
1660978.31997159476062.3470575961660907.97628026476115.331531674
#Sta/Elev= 30
       0 1146.81     6.7 1144.38    21.3 1140.84    61.4 1134.31   102.5 1120.49
   122.3 1115.41   137.6 1113.39   148.4 1110.91   155.7  1107.8   170.5 1095.68
   173.8 1094.25   191.3 1094.71   197.7 1093.67   207.1 1094.56  213.861093.628
   217.1 1093.12  221.611093.619   228.5 1094.37   263.8 1094.42   318.6    1092
   326.5 1093.09   338.2 1097.13   354.6 1104.69   362.8 1109.37   366.9 1112.61
   375.1  1120.5   387.4 1130.77   391.5 1132.53   403.8 1135.41   428.4 1149.78
#Mann= 3, -1 ,  0
       0     0.1       0  213.86   0.045       0  221.61     0.1       0
Bank Sta=213.86,221.61
XS Rating Curve= 0 ,0
Exp/Cntr(USF)=0,0
Exp/Cntr=0.3,0.1

Type RM Length L Ch R = 1 ,23381   ,292.8,293.8,291.2
XS GIS Cut Line= 3
1661149.26467111475705.0872172291660857.88414613475833.629517834
1660712.30081859475932.849285096
#Sta/Elev= 30
       0 1144.59    12.8 1141.81    23.6 1137.83    52.2 1120.95    73.8 1111.61
    98.9 1103.24   113.2 1101.39   131.1 1096.66   145.5 1094.55   170.6 1093.08
   213.6 1091.69   248.4 1092.14   260.2 1089.91   268.4 1090.64  275.19 1089.38
   281.7 1088.47287.4457 1089.38   300.7 1099.96   317.6 1109.17   332.3 1119.58
   334.7 1121.91   345.3 1135.39     354 1142.79     381 1155.91   396.9  1161.3
   412.3 1170.99   424.4 1175.41   440.9 1182.78   452.5 1185.54   494.7 1198.55
#Mann= 3, -1 ,  0
       0     0.1       0  275.19   0.045       0287.4457     0.1       0
Bank Sta=275.19,287.4457
XS Rating Curve= 0 ,0
Exp/Cntr(USF)=0,0
Exp/Cntr=0.3,0.1

Type RM Length L Ch R = 1 ,23087   ,183.7,181.9,180.4
XS GIS Cut Line= 6
1660876.59117243475443.573360756  1660827.880968475519.877670094
1660781.55953833475582.8667173391660699.17157976 475639.84265326
1660638.26586168475685.0692688381660570.45628601475742.465807587
#Sta/Elev= 30
       0 1107.54    29.6 1101.13    54.5    1095    65.2 1093.35    85.6 1091.63
    93.5  1092.1     122 1091.67   177.6 1090.02   190.6 1087.57   206.4 1086.77
  209.881085.966   217.9 1084.81  221.861085.967     223 1086.64   227.7 1091.48
   230.5 1093.81   252.5 1106.81   272.3 1117.24     296 1133.85   302.8 1137.53
   307.2 1138.74   317.1 1139.94   331.1 1142.66   348.3 1147.53   359.2  1151.4
   366.2 1154.34   378.3 1160.55   391.2 1166.53   417.4 1176.15   433.6 1183.26
#Mann= 3, -1 ,  0
       0     0.1       0  209.88   0.045       0  221.86     0.1       0
Bank Sta=209.88,221.86
XS Rating Curve= 0 ,0
Exp/Cntr(USF)=0,0
Exp/Cntr=0.3,0.1

Type RM Length L Ch R = 1 ,22905   ,410.8,413.4,408.7
XS GIS Cut Line= 2
 1660769.4734841475289.1393089091660499.76747451475629.220589214
#Sta/Elev= 30
       0 1140.24    25.4 1135.72    33.8 1133.46    44.1 1129.78    51.1 1125.09
    76.8 1110.34      84 1105.36      94 1099.72   115.1 1086.11   121.7 1083.19
   130.1 1081.93   167.8 1081.19   228.6 1083.08   242.6 1080.49   251.5 1079.65
   257.7 1080.46   263.6 1081.74   282.3 1081.83     285 1082.22   289.2 1083.81
   297.6 1088.97   317.3 1102.34   331.1 1112.95   343.6 1124.22   352.3 1130.95
     358  1132.9   372.9 1134.62   389.7 1139.31   421.4 1152.25     434 1159.15
#Mann= 3, -1 ,  0
       0     0.1       0   242.6   0.045       0   257.7     0.1       0
Bank Sta=242.6,257.7
XS Rating Curve= 0 ,0
Exp/Cntr(USF)=0,0
Exp/Cntr=0.3,0.1

Type RM Length L Ch R = 1 ,22492   ,248.9,263.8,273.4
XS GIS Cut Line= 6
1660514.13848525475058.2614673381660446.29150809475117.297110423
1660398.64068475475175.6467312571660346.51972601475260.993345335
1660301.69927759475321.5654026721660245.21841942475389.643022418
#Sta/Elev= 30
       0 1130.86    30.4 1125.84    39.1 1123.48    43.4 1122.12    70.7 1110.22
    89.9  1103.9   112.6  1097.5   158.9 1087.45   178.2 1078.76     189 1077.52
   197.3 1074.87   206.2 1075.54  211.941073.901   214.2    1073   217.8 1072.78
  225.771073.902   256.2 1075.47   292.4 1075.69   297.8 1076.44   304.6 1078.58
   313.4 1083.59     325 1088.24   337.3 1090.57   362.4 1097.03     384 1104.55
   393.2 1109.09   404.5 1117.11   409.1 1119.73   418.1  1123.3   429.1 1126.07
#Mann= 3, -1 ,  0
       0     0.1       0  211.94   0.045       0  225.77     0.1       0
Bank Sta=211.94,225.77
XS Rating Curve= 0 ,0
Exp/Cntr(USF)=0,0
Exp/Cntr=0.3,0.1

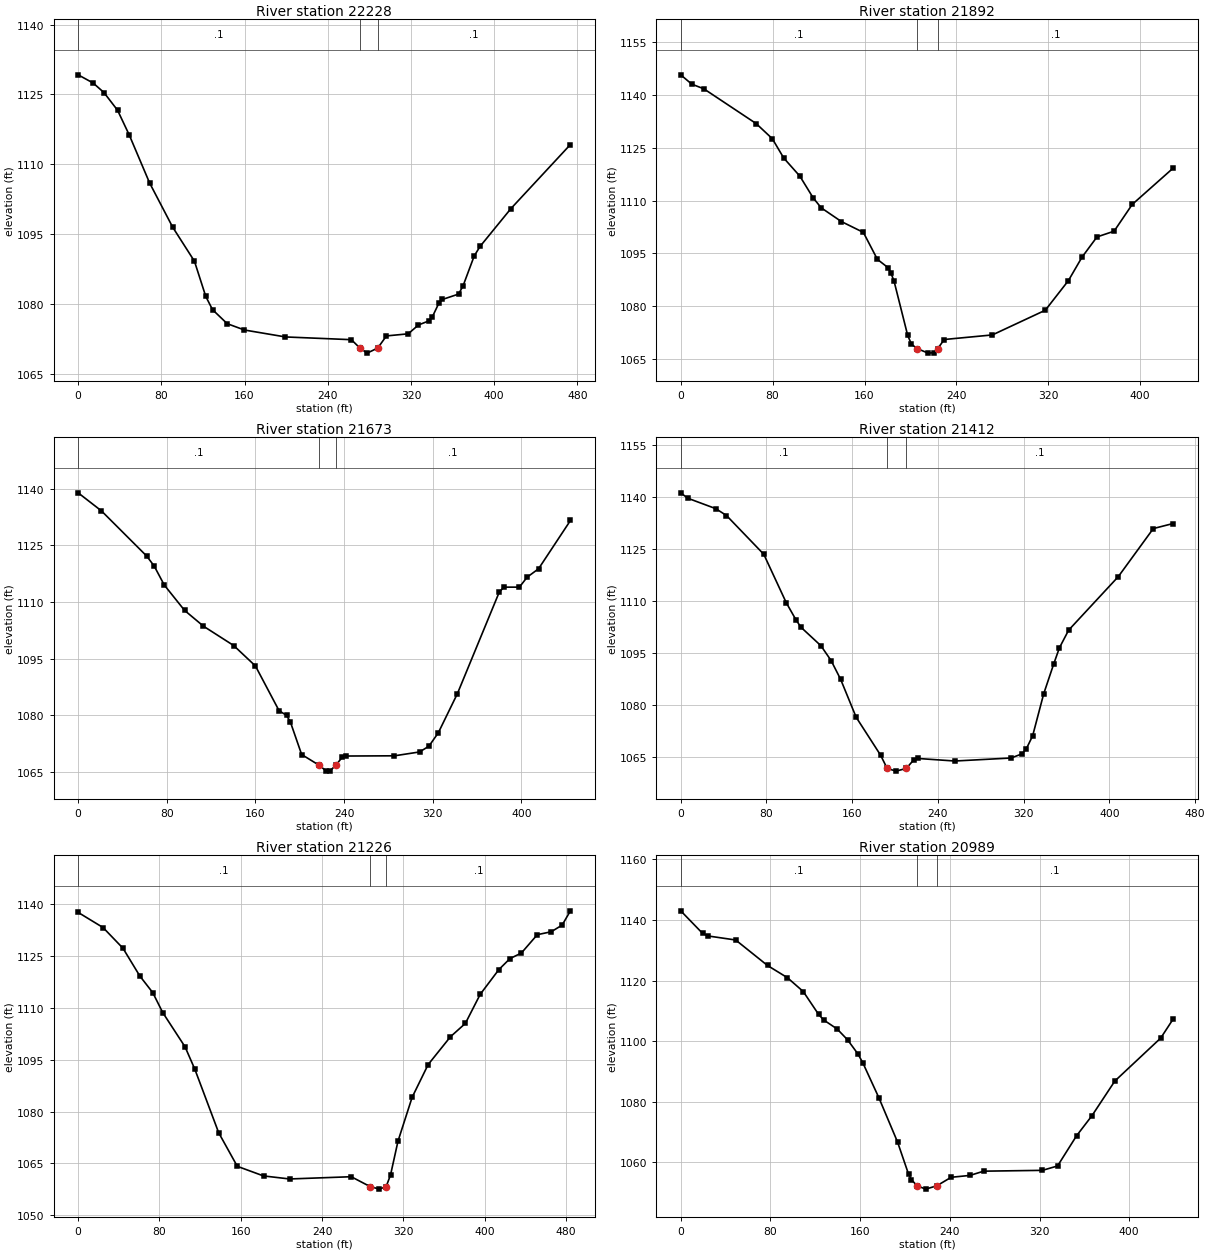
Type RM Length L Ch R = 1 ,22228   ,345.2,336.2,320.4
XS GIS Cut Line= 5
1660481.82818243475015.1162124281660340.13512625475065.073261363
1660235.75251117475060.2182560111660192.08030238475035.893655514
1660024.14629733475050.064257716
#Sta/Elev= 30
       0 1129.22    14.4 1127.46    24.8 1125.41    37.9  1121.6    49.2 1116.25
    68.7 1105.97    90.9 1096.46   111.8 1089.15   122.7 1081.57   129.2 1078.73
   143.3 1075.72   159.9 1074.36   199.3 1072.87   262.7 1072.28  270.771070.504
   277.8 1069.39  288.021070.484   296.4 1073.09   317.3 1073.54   327.2 1075.45
     337  1076.3   340.3 1077.08   346.9 1080.18   350.2 1080.93   365.7 1082.08
     370 1083.82   380.8 1090.29   386.4 1092.33   416.1 1100.47   473.3 1114.24
#Mann= 3, -1 ,  0
       0     0.1       0  270.77   0.045       0  288.02     0.1       0
Bank Sta=270.77,288.02
XS Rating Curve= 0 ,0
Exp/Cntr(USF)=0,0
Exp/Cntr=0.3,0.1

Type RM Length L Ch R = 1 ,21892   ,214.4,218.5,221.9
XS GIS Cut Line= 6
1660291.24687067474634.4066720011660229.76831909474696.852741346
1660181.27071267474754.0685061661660116.84006725474830.583445013
1660067.82441726474887.4484887571659992.84097143474938.708556846
#Sta/Elev= 30
       0 1145.74     9.6 1143.09    20.1 1141.77    65.7 1131.88    79.7  1127.6
    89.7 1122.09   103.7 1116.95   115.3 1110.78   122.3 1107.95   139.9 1104.04
     159 1100.97   171.2 1093.31   180.5 1090.94   182.8 1089.57   185.7 1087.14
   197.6 1071.68   200.9 1069.19  205.851067.947   215.4 1066.66   220.1 1066.79
  223.771067.948   229.4 1070.53   271.3 1071.83   317.4 1078.85   337.5 1087.26
   349.4 1093.95   362.4 1099.68   377.3 1101.31   393.1 1108.92   428.6  1119.2
#Mann= 3, -1 ,  0
       0     0.1       0  205.85   0.045       0  223.77     0.1       0
Bank Sta=205.85,223.77
XS Rating Curve= 0 ,0
Exp/Cntr(USF)=0,0
Exp/Cntr=0.3,0.1

Type RM Length L Ch R = 1 ,21673   ,264.1,260.8,253
XS GIS Cut Line= 4
1660229.25597944474557.3288442371660045.55366882474609.658520492
1659991.01679437474634.2502448591659840.93621044474756.337956151
#Sta/Elev= 30
       0  1138.9      21 1134.12    61.9 1122.13    68.7 1119.46    77.7 1114.48
      96 1107.76   113.1 1103.56   140.4 1098.43     160 1093.02   181.3 1081.19
   188.1 1079.92   191.6 1078.13   201.7 1069.56   217.1 1066.79   224.1 1065.16
   227.6 1065.31  232.681066.766   238.4 1068.86   241.4 1069.16   285.5 1069.22
   308.1 1070.24   316.5 1071.75     325 1075.29   342.3 1085.71     380 1112.56
   384.2 1113.91   398.2 1113.91   405.3 1116.57   415.5 1118.77   444.3 1131.57
#Mann= 3, -1 ,  0
       0     0.1       0   217.1   0.045       0  232.68     0.1       0
Bank Sta=217.1,232.68
XS Rating Curve= 0 ,0
Exp/Cntr(USF)=0,0
Exp/Cntr=0.3,0.1

Type RM Length L Ch R = 1 ,21412   ,175.4,186,183.9
XS GIS Cut Line= 4
1660026.74566418474285.485498677 1659895.8224316474414.171826015
1659825.29046526474528.9914361281659732.56590143474635.291184679
#Sta/Elev= 30
       0 1141.26     6.5 1139.71    32.7 1136.69    42.7 1134.71    77.5 1123.51
    98.5 1109.51   107.7 1104.49   112.3 1102.41   130.8 1097.11   140.3 1092.83
   149.2 1087.41   163.7 1076.45   186.5  1065.5   192.61061.683   200.9 1060.89
   210.5 1061.67   217.3  1064.1   221.1 1064.55   255.8 1063.81   308.3 1064.68
   318.4 1065.87   322.5 1067.34   328.4 1071.09   338.7 1083.21     348 1091.78
   353.4 1096.52     362 1101.61   408.3 1117.05     441 1130.94   459.4 1132.39
#Mann= 3, -1 ,  0
       0     0.1       0   192.6   0.045       0   210.5     0.1       0
Bank Sta=192.6,210.5
XS Rating Curve= 0 ,0
Exp/Cntr(USF)=0,0
Exp/Cntr=0.3,0.1

Type RM Length L Ch R = 1 ,21226   ,229.2,237.8,222
XS GIS Cut Line= 2
1659984.69111263474270.8421020991659552.42096927 474489.54409862
#Sta/Elev= 30
       0 1137.65    24.5 1133.27    44.1 1127.28    60.7 1119.24    73.4 1114.44
    83.2 1108.68   105.2 1098.74   114.9  1092.2   138.3 1073.87   156.6 1064.17
   182.4 1061.39   208.1 1060.51   268.7 1061.16  287.14 1058.33   296.4 1057.57
  303.11 1058.33   307.4 1061.71   314.7 1071.44   328.6 1084.13   344.4 1093.63
   366.3 1101.66     381 1105.53   395.6 1113.94     414 1121.12   424.9 1124.29
   436.1 1125.89   451.8 1131.21   465.5 1132.05   476.2 1133.98   484.4 1138.11
#Mann= 3, -1 ,  0
       0     0.1       0  287.14   0.045       0  303.11     0.1       0
Bank Sta=287.14,303.11
XS Rating Curve= 0 ,0
Exp/Cntr(USF)=0,0
Exp/Cntr=0.3,0.1

Type RM Length L Ch R = 1 ,20989   ,292.6,298.4,301.5
XS GIS Cut Line= 6
1659861.74543309474068.8789316711659801.05067259474131.906036586
1659749.02748267474185.9298786671659674.78189626474253.261108845
1659597.56223442474279.7374338361659506.16215476 474304.66487743
#Sta/Elev= 30
       0 1143.02    19.5 1135.57    24.3 1134.72      49 1133.39    77.4 1124.97
    95.2 1120.93   109.3 1116.36     123 1108.81   127.5 1106.98   139.5 1104.01
   148.8 1100.43   158.1 1095.74   162.5 1092.77   176.7 1081.33   193.4 1066.67
   203.2 1056.07   205.8 1054.21  210.881052.237   218.5 1051.13  228.451052.238
   241.2 1055.04     258 1055.66   270.2 1057.06   322.6 1057.33   336.1 1058.78
   353.1 1068.77   366.8 1075.38   387.2 1086.82   428.1    1101   439.1 1107.22
#Mann= 3, -1 ,  0
       0     0.1       0  210.88   0.045       0  228.45     0.1       0
Bank Sta=210.88,228.45
XS Rating Curve= 0 ,0
Exp/Cntr(USF)=0,0
Exp/Cntr=0.3,0.1

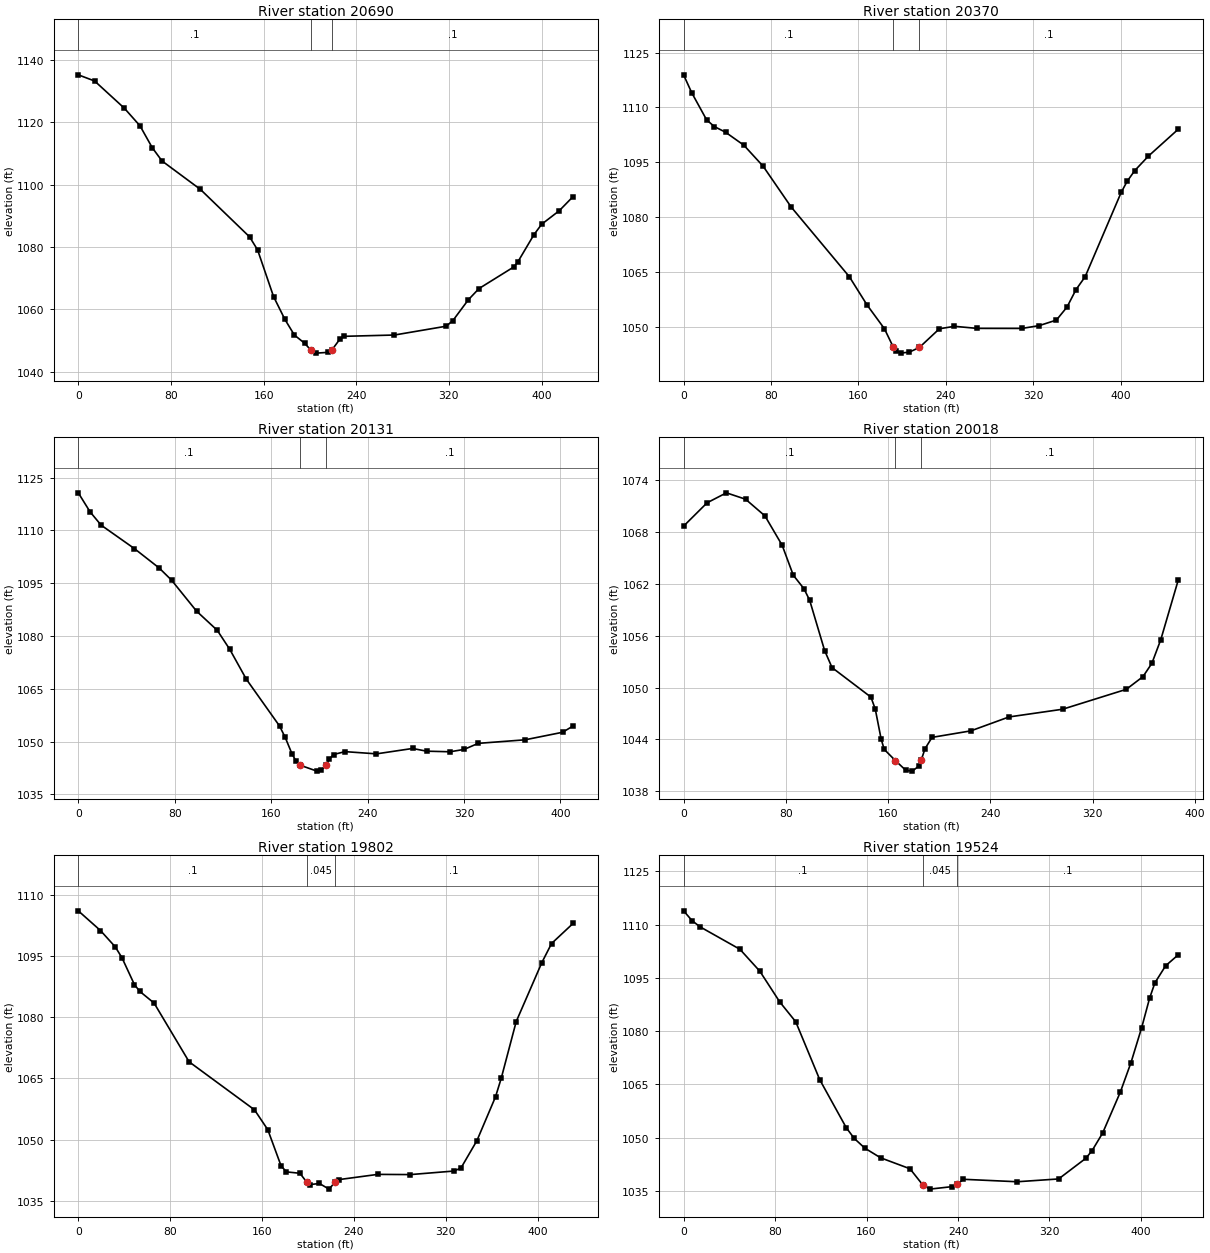
Type RM Length L Ch R = 1 ,20690   ,318.8,320.1,321.1
XS GIS Cut Line= 6
1659733.28604434473915.0567327591659651.95123325473949.175759003
1659580.59179592473973.921444416    1659483.1435473996.663196832
1659410.06064093474013.7359973341659327.95450592474046.416050091
#Sta/Elev= 30
       0 1135.25    14.1 1133.27    39.8 1124.53    53.3 1118.88    63.9 1111.85
    72.3 1107.61   105.4  1098.5   147.9 1083.25   154.8 1079.09   168.6  1064.1
   178.4 1056.76   186.6 1051.74   195.5 1049.09     2011046.839   205.6 1045.94
   215.7 1046.19  218.741046.838   225.8 1050.39   229.2 1051.33     273 1051.75
   317.7 1054.58   323.5 1056.41   336.8 1063.06     346 1066.66   375.8 1073.54
   379.3 1075.07   393.4 1083.93   400.1  1087.3   415.3 1091.64   427.2 1096.17
#Mann= 3, -1 ,  0
       0     0.1       0     201   0.045       0  218.74     0.1       0
Bank Sta=201,218.74
XS Rating Curve= 0 ,0
Exp/Cntr(USF)=0,0
Exp/Cntr=0.3,0.1

Type RM Length L Ch R = 1 ,20370   ,238.5,239.1,238.5
XS GIS Cut Line= 3
1659560.12841134473678.9918382961659226.74203822473781.842838208
1659163.49705084473864.286921828
#Sta/Elev= 30
       0 1118.91     7.5 1113.99    21.1  1106.6    28.1 1104.78    38.4 1103.23
    55.2 1099.67    72.8 1093.94    98.4 1082.82   151.7 1063.75     168 1055.99
   183.8 1049.54  192.091044.415   194.3 1043.45   198.6 1042.87   206.7 1043.15
  215.851044.431   234.1 1049.52   247.9  1050.2   268.5 1049.63   309.7 1049.62
   325.5 1050.39   341.2  1051.9   350.9 1055.45   359.2 1060.25   367.5 1063.74
   400.5 1086.79   405.9 1089.79   412.9 1092.74   425.4  1096.7   452.8 1104.07
#Mann= 3, -1 ,  0
       0     0.1       0  192.09   0.045       0  215.85     0.1       0
Bank Sta=192.09,215.85
XS Rating Curve= 0 ,0
Exp/Cntr(USF)=0,0
Exp/Cntr=0.3,0.1

Type RM Length L Ch R = 1 ,20131   ,117.3,113.2,110.1
XS GIS Cut Line= 3
1659479.06987717473454.4503895741659216.27693369473538.331773554
1659102.66543894473610.533471156
#Sta/Elev= 30
       0 1120.69     9.8 1115.28    18.9 1111.52    46.6 1104.83    67.1 1099.33
    77.4 1095.87    98.1 1087.08   115.3 1081.62   125.7  1076.2   139.4 1067.74
     167 1054.42   171.7 1051.17   177.3 1046.53   180.8 1044.35  183.851043.308
     198  1041.6   201.4  1041.8  205.681043.338   208.3 1044.99   211.8 1046.32
   221.3 1047.14   247.4 1046.51   277.4 1048.04     289 1047.27   308.5  1047.1
   320.1 1047.77   331.8 1049.49   370.7  1050.5   401.8 1052.64   410.5 1054.42
#Mann= 3, -1 ,  0
       0     0.1       0  183.85   0.045       0  205.68     0.1       0
Bank Sta=183.85,205.68
XS Rating Curve= 0 ,0
Exp/Cntr(USF)=0,0
Exp/Cntr=0.3,0.1

Type RM Length L Ch R = 1 ,20018   ,213.7,216,214.7
XS GIS Cut Line= 2
1659365.12713681473312.0665969721659072.67617938473565.323096188
#Sta/Elev= 30
       0 1068.64    18.4 1071.34    33.5 1072.49    48.5 1071.75    63.6 1069.83
    77.1 1066.43    85.8 1062.97    94.1 1061.42    98.6 1060.08   110.3 1054.27
   116.1  1052.3   146.5 1048.89   149.9 1047.51   154.5 1044.04   156.9 1042.85
  165.611041.565   173.8 1040.43   178.8 1040.34   183.8  1040.9  185.811041.598
   188.8 1042.93   194.3 1044.24   224.6 1044.99   254.5  1046.6   296.4 1047.49
   346.2 1049.79   359.2 1051.25   366.2 1052.79   373.2 1055.54   386.9 1062.45
#Mann= 3, -1 ,  0
       0     0.1       0  165.61   0.045       0  185.81     0.1       0
Bank Sta=165.61,185.81
XS Rating Curve= 0 ,0
Exp/Cntr(USF)=0,0
Exp/Cntr=0.3,0.1

Type RM Length L Ch R = 1 ,19802   ,277.3,277.8,272.9
XS GIS Cut Line= 6
1659250.91758651473130.0924234241659187.30977409473193.042100668
1659131.17766851 473245.82381925 1659051.6466596473307.606504083
1658993.14087109473354.6864624171658932.98187068473419.481280342
#Sta/Elev= 30
       0 1106.02    19.3  1101.2    32.1 1097.23      38 1094.56    48.9 1087.95
    53.6 1086.29      66 1083.44    96.5 1069.06   153.4 1057.31     165 1052.45
   176.6 1043.57   181.3 1042.11     193 1041.77  198.891039.608   201.6    1039
     210 1039.27   218.3 1037.89  223.661039.608   226.6 1040.21   260.8  1041.5
   289.2 1041.45   327.1 1042.32   333.2 1043.05   347.1 1049.76   363.3 1060.49
   368.3 1065.05   381.3  1078.9   403.6 1093.33   412.1 1098.02   430.8 1102.93
#Mann= 3, -1 ,  0
       0     0.1       0  198.89   0.045       0  223.66     0.1       0
Bank Sta=198.89,223.66
XS Rating Curve= 0 ,0
Exp/Cntr(USF)=0,0
Exp/Cntr=0.3,0.1

Type RM Length L Ch R = 1 ,19524   ,329.3,334,326.5
XS GIS Cut Line= 6
1659084.62918089472933.9326785371659018.91113646 472991.70323229
1658962.58152471473041.2205217051658893.57903805473114.187239291
1658846.58110055473175.8058824551658780.29744047473239.961922126
#Sta/Elev= 30
       0  1113.9     7.4 1111.15    14.2 1109.43    49.3 1103.06    66.7 1096.88
    84.1 1088.23    98.1 1082.63   119.1  1066.3   142.3 1052.77   149.2 1049.78
   158.5 1047.02   172.3  1044.3     198 1041.21   209.11036.692   215.3 1035.47
   235.1 1036.18   239.2 1036.83   244.8 1038.24   291.8 1037.55     328 1038.34
   351.8 1044.16   357.3 1046.34   366.5 1051.28     382 1062.84   391.3 1071.14
   400.6 1080.95   407.5 1089.21   412.2 1093.61   421.6 1098.42   432.7 1101.53
#Mann= 3, -1 ,  0
       0     0.1       0   209.1   0.045       0   239.2     0.1       0
Bank Sta=209.1,239.2
XS Rating Curve= 0 ,0
Exp/Cntr(USF)=0,0
Exp/Cntr=0.3,0.1

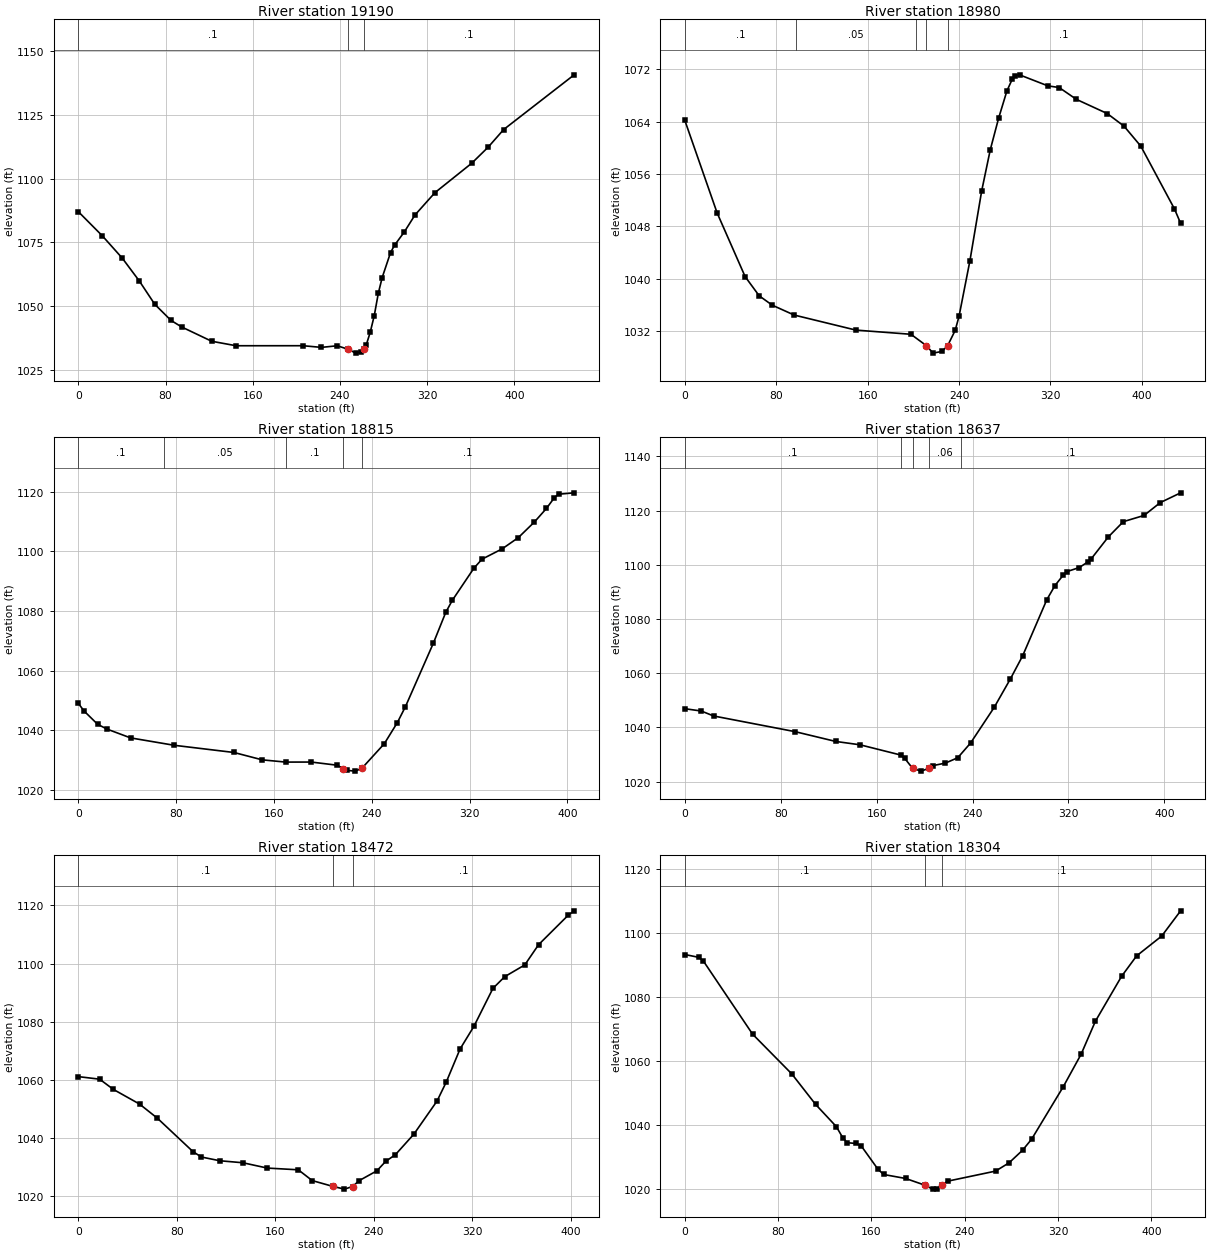
Type RM Length L Ch R = 1 ,19190   ,210.1,209.5,208.8
XS GIS Cut Line= 2
1658899.37660225472817.8398899871658499.25251167473034.070981274
#Sta/Elev= 30
       0 1087.06    22.1 1077.56    40.3 1068.87      56 1059.89    70.1 1050.81
      85  1044.5    94.7 1041.95   122.3 1036.34   144.7 1034.58   206.1 1034.59
     223 1033.94   237.5 1034.57   247.2 1033.24   254.5 1031.69   259.3  1032.2
   261.7 1033.26   264.2 1035.04   267.7  1039.8   271.4 1046.28   275.2 1055.21
   278.7 1061.26   286.4 1071.07   290.1 1073.95     299 1079.12   308.8 1085.76
   327.1  1094.5   360.9 1106.04   375.9  1112.3   390.1 1119.19   454.8 1140.62
#Mann= 3, -1 ,  0
       0     0.1       0   247.2   0.045       0   261.7     0.1       0
Bank Sta=247.2,261.7
XS Rating Curve= 0 ,0
Exp/Cntr(USF)=0,0
Exp/Cntr=0.3,0.1

Type RM Length L Ch R = 1 ,18980   ,164.8,165.5,165.3
XS GIS Cut Line= 6
1658762.01564636 472625.655078641658691.77595744472677.833780056
1658631.57036919472722.5584281441658545.73425478472776.104908978
1658474.60349152472810.6386325561658393.26638386472851.851148566
#Sta/Elev= 30
       0 1064.22    28.3 1050.06    52.8 1040.33    65.1  1037.4    76.5 1035.97
    95.7 1034.46   149.7 1032.16   197.9 1031.52   211.4 1029.78   217.3 1028.64
     225  1028.9     2301029.773   236.6 1032.11     240 1034.28   249.5 1042.75
   259.8 1053.43   267.3  1059.7   274.6 1064.53   281.9 1068.72   286.5 1070.48
   289.2 1071.04   292.9 1071.17   317.8 1069.48   327.6 1069.23   342.7 1067.42
   369.7 1065.25   384.4 1063.32   399.1 1060.26   428.5 1050.68   433.9 1048.48
#Mann= 5, -1 ,  0
       0     0.1       0    97.5    0.05       0   202.5     0.1       0
   211.4   0.045       0     230     0.1       0
Bank Sta=211.4,230
XS Rating Curve= 0 ,0
Exp/Cntr(USF)=0,0
Exp/Cntr=0.3,0.1

Type RM Length L Ch R = 1 ,18815   ,174.1,177.5,178.5
XS GIS Cut Line= 3
1658693.70543864 472498.193808461658475.23019777472631.706455659
1658326.34336695472645.462304158
#Sta/Elev= 30
       0 1049.03     4.7 1046.46    15.8 1042.01    23.5  1040.4    42.7 1037.46
    78.4 1034.98   127.3 1032.57   150.4  1030.1   169.6 1029.35   190.6 1029.36
   211.9 1028.29   216.41027.195   219.6 1026.58   226.4 1026.32  231.861027.224
   250.3 1035.51     261 1042.61   267.6 1047.94   290.4 1069.18   300.6 1079.56
     306  1083.6   323.6 1094.33   330.2 1097.34   346.7  1100.8   359.9 1104.56
   373.1 1109.81   382.9 1114.34   389.5    1118   392.8 1119.11   405.6 1119.58
#Mann= 5, -1 ,  0
       0     0.1       0      70    0.05       0     170     0.1       0
   216.4   0.045       0  231.86     0.1       0
Bank Sta=216.4,231.86
XS Rating Curve= 0 ,0
Exp/Cntr(USF)=0,0
Exp/Cntr=0.3,0.1

Type RM Length L Ch R = 1 ,18637   ,165.9,165.7,162.5
XS GIS Cut Line= 3
1658654.23613443472396.5503755971658415.65309505472459.645472116
  1658253.594778472499.186533004
#Sta/Elev= 30
       0 1046.91    13.8 1046.05      24 1044.23    91.9 1038.45   125.8 1034.84
   146.2 1033.59   180.1 1029.82   183.5 1028.56     190 1024.92   197.1 1023.88
   203.5 1024.89   207.3 1025.94   217.4 1026.85   227.7 1028.82   238.4 1034.26
   258.1 1047.41   271.6 1057.91   281.8  1066.4     302 1087.14   308.8 1092.35
   315.5 1096.09   318.9 1097.51     329 1098.98     336 1100.99   339.2  1102.3
   353.3 1110.29   365.8 1115.91   383.1 1118.21   396.6 1122.94   413.6 1126.55
#Mann= 5, -1 ,  0
       0     0.1       0     180    0.06       0     190   0.045       0
   203.5    0.06       0     230     0.1       0
Bank Sta=190,203.5
XS Rating Curve= 0 ,0
Exp/Cntr(USF)=0,0
Exp/Cntr=0.3,0.1

Type RM Length L Ch R = 1 ,18472   ,166.2,167.3,166
XS GIS Cut Line= 2
1658573.94863994472198.8018117111658221.96075187472394.620360936
#Sta/Elev= 30
       0 1061.15    17.3 1060.27    28.5 1056.75    49.7 1051.73    64.2 1046.87
    93.1  1035.4    99.9 1033.54   114.9 1032.25   133.7 1031.56   153.5 1029.73
   178.7 1029.14     190 1025.44   206.5 1023.47   216.2  1022.5   222.8  1023.4
   228.2 1025.43   242.5 1028.78   249.7 1032.04   257.6 1034.34   272.6 1041.39
   291.4 1052.76   298.9 1059.29   310.1 1070.63   321.4 1078.45   336.8 1091.46
   346.4 1095.49   362.7 1099.53   373.9 1106.48   398.2  1116.7   402.8 1118.11
#Mann= 3, -1 ,  0
       0     0.1       0   206.5   0.045       0   222.8     0.1       0
Bank Sta=206.5,222.8
XS Rating Curve= 0 ,0
Exp/Cntr(USF)=0,0
Exp/Cntr=0.3,0.1

Type RM Length L Ch R = 1 ,18304   ,295.8,300,301.3
XS GIS Cut Line= 6
1658503.29900301472043.2547020911658428.87165843472089.263796419
1658365.07683851472128.7000692491658280.01729734 472181.28165701
1658216.22214934 472220.717929841658141.79513285472266.727352262
#Sta/Elev= 30
       0 1093.29    11.8 1092.42    15.7 1091.37    58.1 1068.39    91.7 1055.96
   112.1 1046.43   129.9 1039.47   135.3 1036.07   139.1 1034.45   146.8  1034.2
   151.3 1033.41   165.6 1026.14   170.4 1024.51   189.3 1023.26  205.481021.206
   212.4 1019.93   216.3  1020.1  220.391021.187   225.2 1022.41   266.4 1025.57
     278 1028.17   289.5 1032.09   297.3 1035.56   324.3 1051.88   339.7 1062.11
     352 1072.47   374.4 1086.48   387.3 1092.87   408.8 1099.07     425 1106.95
#Mann= 3, -1 ,  0
       0     0.1       0  205.48   0.045       0  220.39     0.1       0
Bank Sta=205.48,220.39
XS Rating Curve= 0 ,0
Exp/Cntr(USF)=0,0
Exp/Cntr=0.3,0.1

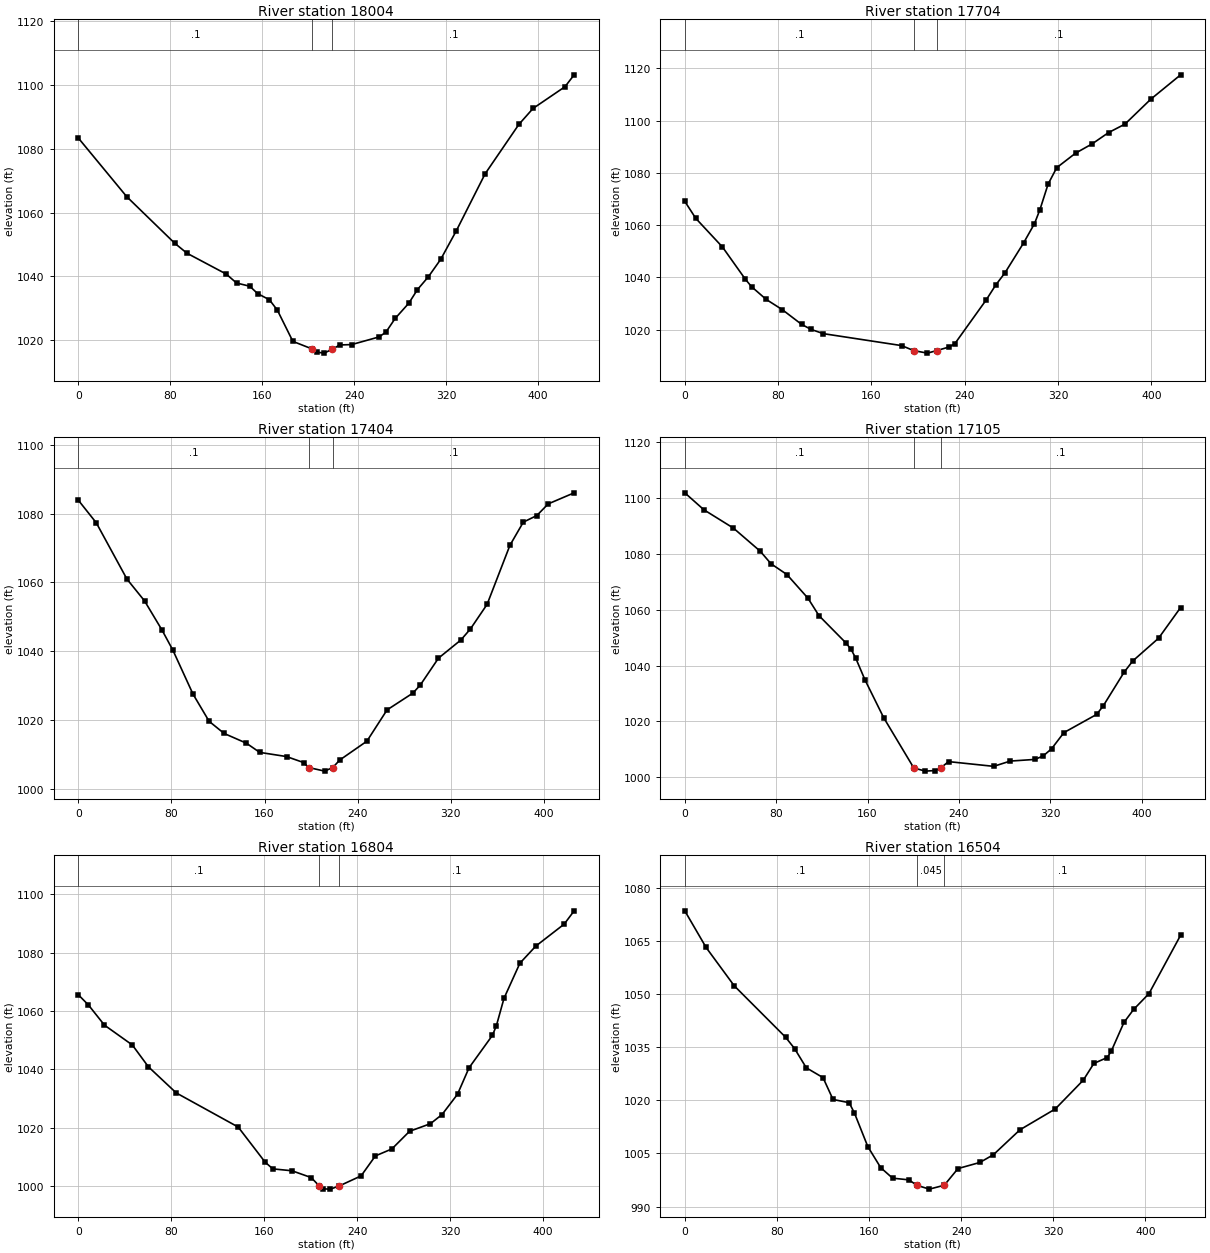
Type RM Length L Ch R = 1 ,18004   ,301.9,300,296.7
XS GIS Cut Line= 6
1658332.93057734471852.0943232631658255.30507642471896.478420839
1658183.34951167471917.6532472521658087.05344443471944.617760256
1658019.84819825471981.5845498441657945.36967267 472032.78621909
#Sta/Elev= 30
       0 1083.34    42.1 1064.99    83.7 1050.46    94.5 1047.28   128.7 1040.75
   137.7 1037.94   149.2 1036.94     156 1034.64   166.3 1032.69   173.2 1029.45
   186.7 1019.67  203.591017.282   207.7 1016.29     214 1015.99  221.111017.256
   227.6 1018.55   237.8 1018.66   261.7 1021.06   267.7 1022.57   275.7 1026.84
   287.6 1031.62   295.1 1035.87   304.7 1039.93   315.4 1045.38   328.9 1054.27
     354 1072.13   383.4 1087.61   395.7  1092.6   423.5  1099.4   431.5 1103.13
#Mann= 3, -1 ,  0
       0     0.1       0  203.59   0.045       0  221.11     0.1       0
Bank Sta=203.59,221.11
XS Rating Curve= 0 ,0
Exp/Cntr(USF)=0,0
Exp/Cntr=0.3,0.1

Type RM Length L Ch R = 1 ,17704   ,298.1,300,300.3
XS GIS Cut Line= 6
1658102.96450184471589.3363185821658034.02172634471643.360160679
1657974.13667551471688.556920677 1657892.7395286471746.647355676
1657831.69142234471790.2151819171657760.46912384471841.044476584
#Sta/Elev= 30
       0 1069.07     9.4 1062.57    32.3  1051.6      52 1039.22    57.3 1036.39
    69.7 1031.58    83.6 1027.63   100.2 1021.98   108.3 1020.07   118.8 1018.45
   185.9 1013.88  196.291011.961     208    1011  215.931011.962   226.9 1013.39
   231.6 1014.66   258.5 1031.42   266.5    1037   274.6 1041.79   290.4 1053.11
   299.8 1060.54   304.5 1065.93   311.5 1075.69   318.9 1081.96     335  1087.5
   349.2 1091.05   363.3 1095.38   377.4 1098.63   399.5 1108.15   425.1 1117.48
#Mann= 3, -1 ,  0
       0     0.1       0  196.29   0.045       0  215.93     0.1       0
Bank Sta=196.29,215.93
XS Rating Curve= 0 ,0
Exp/Cntr(USF)=0,0
Exp/Cntr=0.3,0.1

Type RM Length L Ch R = 1 ,17404   ,303.7,298.9,295.4
XS GIS Cut Line= 6
1657938.99468543471372.9899665121657862.08079726471416.808448419
1657797.58650367471455.3306810861657712.16607083471507.324343503
1657648.10091026471546.3196723461657573.35794951471591.814332008
#Sta/Elev= 30
       0 1083.88    15.4 1077.32    41.8 1060.92    56.9 1054.59      72 1046.05
    81.3 1040.22    98.5  1027.5   112.4 1019.55   125.3 1016.02   144.4 1013.19
   155.9 1010.51   178.9  1009.3   193.7 1007.54  197.92 1006.11   211.7 1005.06
  218.671006.111   224.7  1008.3     248 1013.78   265.3 1022.87   287.5 1027.76
   293.8 1030.07   309.5 1037.93   328.7  1043.2   336.9  1046.4   351.3 1053.59
   370.9 1070.76   382.4  1077.5     394 1079.42   403.8 1082.81   426.1 1086.03
#Mann= 3, -1 ,  0
       0     0.1       0  197.92   0.045       0  218.67     0.1       0
Bank Sta=197.92,218.67
XS Rating Curve= 0 ,0
Exp/Cntr(USF)=0,0
Exp/Cntr=0.3,0.1

Type RM Length L Ch R = 1 ,17105   ,305.6,301.2,293.4
XS GIS Cut Line= 6
1657683.76980217471099.8153160071657629.51958258471168.484798089
1657584.06626143471228.1421590891657525.27143151471309.064241335
 1657492.4174946471380.3780750931657456.56093901471466.288008258
#Sta/Elev= 30
       0 1101.71    16.7 1095.66    42.6 1089.09      66 1080.86    75.5 1076.36
    89.4 1072.51   107.8 1064.07   117.5 1057.81   140.9 1048.14   145.5 1045.83
   149.6 1042.68   157.8 1034.83   174.1 1021.38   200.51003.389   210.6 1002.26
   218.8 1002.46  224.031003.389   230.9 1005.66   270.4 1003.97   284.9 1005.85
   306.6 1006.45   313.8  1007.7   321.1 1010.24   331.9 1016.02   360.5 1022.51
   366.2 1025.48   384.7 1037.66   392.3 1041.67   414.8 1049.76   434.1 1060.73
#Mann= 3, -1 ,  0
       0     0.1       0   200.5   0.045       0  224.03     0.1       0
Bank Sta=200.5,224.03
XS Rating Curve= 0 ,0
Exp/Cntr(USF)=0,0
Exp/Cntr=0.3,0.1

Type RM Length L Ch R = 1 ,16804   ,295,299.9,306.8
XS GIS Cut Line= 6
1657314.23281159 470996.264342011657288.05208968471080.874409005
1657276.65119384471155.0166491721657264.32083793471254.255952001
1657252.77952242471328.4237826761657232.29826418471414.147692591
#Sta/Elev= 30
       0 1065.56     8.7 1062.06    22.5 1055.15    46.5 1048.35    60.3 1040.89
    84.3 1031.93   137.6 1020.24   160.8 1008.21   167.4 1005.91   183.9 1005.26
   200.5 1002.92  207.361000.057   210.4  999.06     217  998.97  224.571000.056
   243.4 1003.51   255.7 1010.35   269.9 1012.74   285.1 1018.78   303.1 1021.39
   313.1 1024.53   326.4 1031.48   336.3 1040.53   356.5 1051.69   359.9 1055.02
   366.4 1064.34   380.1 1076.38   393.8 1082.24   418.2 1089.76   426.8 1094.32
#Mann= 3, -1 ,  0
       0     0.1       0  207.36   0.045       0  224.57     0.1       0
Bank Sta=207.36,224.57
XS Rating Curve= 0 ,0
Exp/Cntr(USF)=0,0
Exp/Cntr=0.3,0.1

Type RM Length L Ch R = 1 ,16504   ,336.7,340.6,335.9
XS GIS Cut Line= 6
1657176.00146076470889.8265627621657114.10132208470951.694221169
1657062.10437883471005.7433256661656992.77544926471077.809126422
1656944.92055809471135.8431310951656905.41243501471219.756349087
#Sta/Elev= 30
       0 1073.58    18.5 1063.22    42.9  1052.4    87.5 1037.86    95.3 1034.65
   105.5 1029.21     120 1026.44   128.7 1020.26   142.7 1019.35   147.3 1016.42
   158.9 1006.94   170.1 1000.99   180.4  998.02   194.6  997.54  201.39996.0152
   212.3  994.92  225.28996.0134   237.2 1000.73   256.2 1002.46     268 1004.66
     291 1011.69   321.6 1017.56     346 1025.72   355.2 1030.46   366.8 1032.11
   370.4    1034   381.3 1042.04   389.7 1045.71     403 1050.17   430.5 1066.69
#Mann= 3, -1 ,  0
       0     0.1       0  201.39   0.045       0  225.28     0.1       0
Bank Sta=201.39,225.28
XS Rating Curve= 0 ,0
Exp/Cntr(USF)=0,0
Exp/Cntr=0.3,0.1