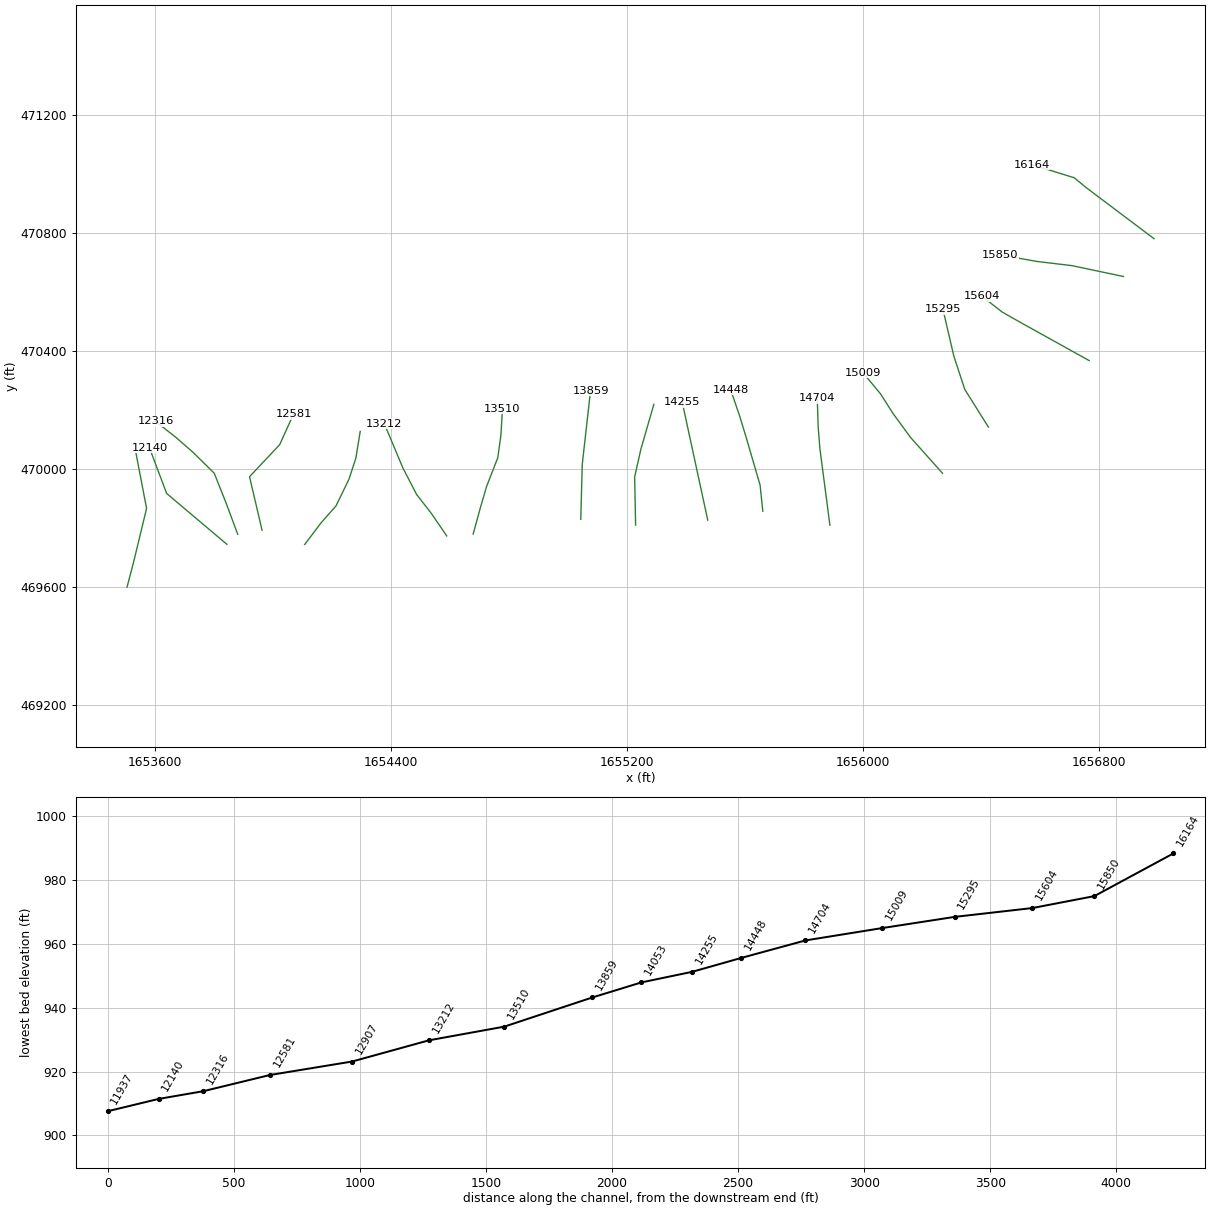
HEC-RAS study MagtyRn.prj: MagtyRn

--- MagtyRn.g01 (geometry) --- (continued)

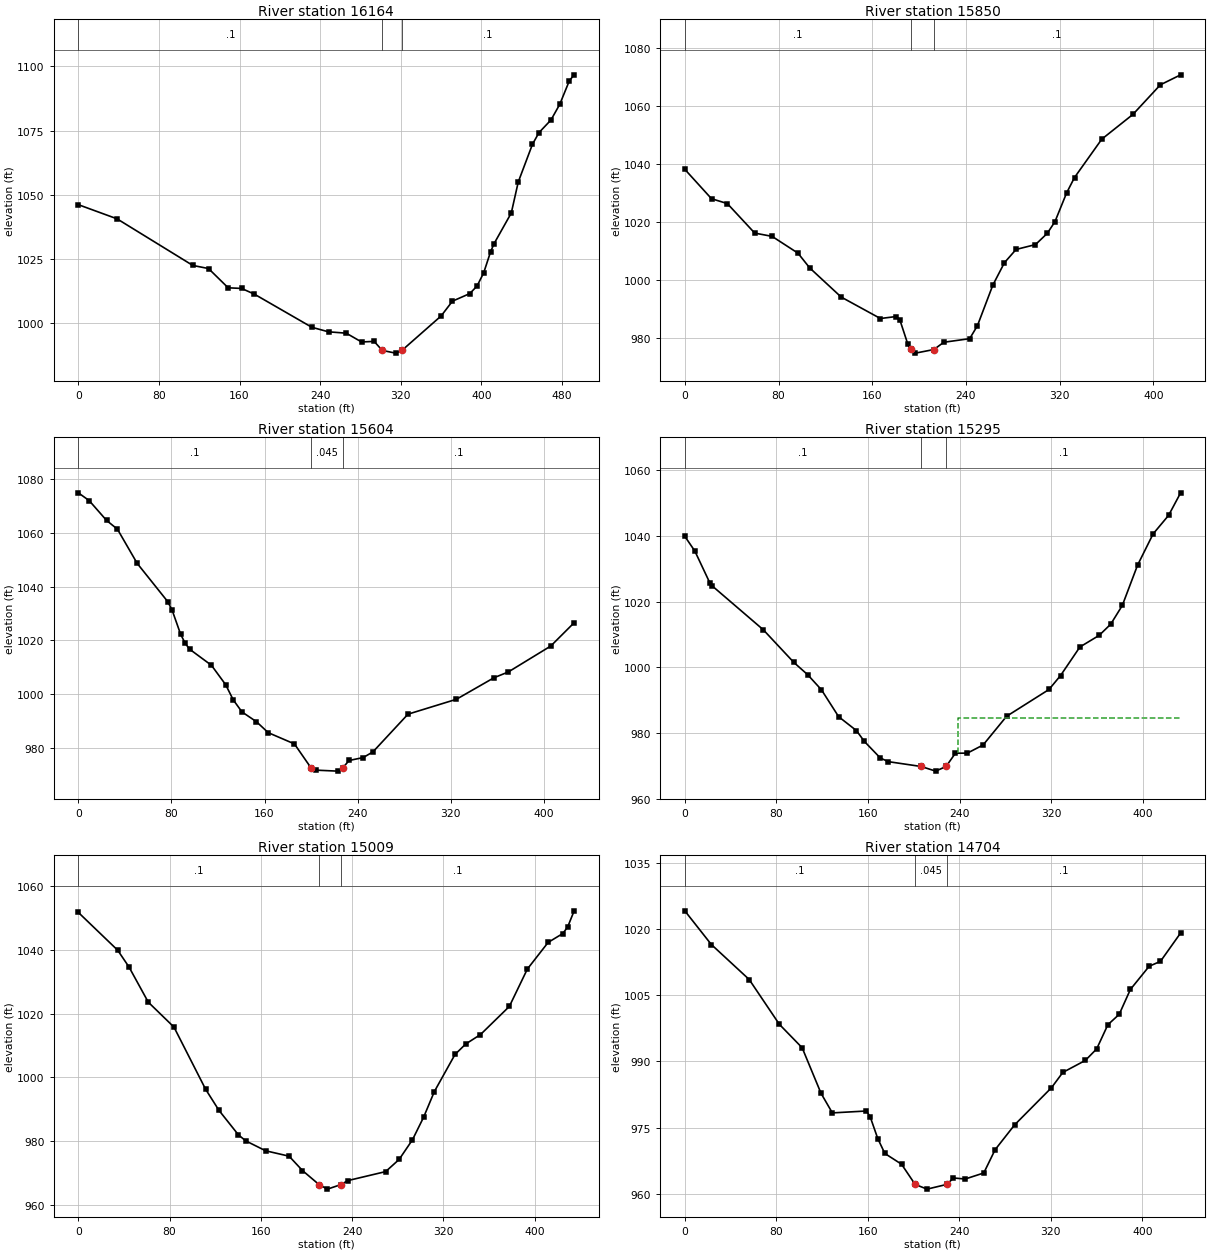
Type RM Length L Ch R = 1 ,16164   ,302.6,314,315.9
XS GIS Cut Line= 4
1656985.51681646470781.4044583151656754.19482278  470955.6429991
1656715.28892079470987.9495227331656570.12568809471032.888732416
#Sta/Elev= 30
       0 1046.17    38.4 1040.66   113.6  1022.5   129.2 1021.29   148.7 1013.79
     162 1013.54   174.7 1011.32   231.8   998.4   248.3  996.64   265.9  996.11
   281.1  992.69   293.6  992.91  301.65989.3925   314.9  988.34  321.21989.4121
   360.1 1002.84   371.3 1008.58   388.5 1011.53   395.7 1014.47   402.3 1019.61
   409.1 1027.76   412.6 1030.98   429.7 1042.93   436.6 1054.99   450.7 1069.68
   457.2 1074.25   469.1 1079.17   477.8 1085.26   487.4  1094.5   492.1 1096.75
#Mann= 3, -1 ,  0
       0     0.1       0  301.65   0.045       0  321.21     0.1       0
Bank Sta=301.65,321.21
XS Rating Curve= 0 ,0
Exp/Cntr(USF)=0,0
Exp/Cntr=0.3,0.1

Type RM Length L Ch R = 1 ,15850   ,250,245.4,242.1
XS GIS Cut Line= 4
1656881.73773146470653.3063816931656707.68970741470690.070488111
1656588.08738089470704.3464170921656465.11607151470726.456810758
#Sta/Elev= 30
       0 1038.24    22.8 1028.12    36.3 1026.45    59.7 1016.28    74.5 1015.16
    96.6 1009.38   106.7 1004.27   133.5  994.26     167  986.87   180.4  987.55
   183.7  986.28   190.3  978.16  192.79976.1996   196.9  974.95  212.61976.1886
   221.1  978.69   243.2  979.93   249.8  984.37     263  998.39   272.9  1006.1
   282.8 1010.65   299.4 1012.33   309.4 1016.17     316 1020.21     326 1030.15
   332.7 1035.42     356 1048.63   382.6 1057.16     406 1067.34   423.3 1070.78
#Mann= 3, -1 ,  0
       0     0.1       0  192.79   0.045       0  212.61     0.1       0
Bank Sta=192.79,212.61
XS Rating Curve= 0 ,0
Exp/Cntr(USF)=0,0
Exp/Cntr=0.3,0.1

Type RM Length L Ch R = 1 ,15604   ,318.1,308.8,298.6
XS GIS Cut Line= 6
1656765.80346225 470368.217369751656689.31444201470410.710723087
1656623.75256525470447.1338785891656536.33640151470495.697429761
1656471.14493084  470532.78692251656401.25136983470587.152627423
#Sta/Elev= 30
       0 1074.91     9.3 1072.02    24.3 1064.61    33.6 1061.36    50.6 1048.61
    76.8 1034.39    80.6  1031.2    87.9 1022.22    91.9  1018.8    95.6 1016.66
   114.4 1010.65   126.6 1003.43   133.1  997.79   140.6  993.29   153.1  989.62
   163.2  985.55   185.7  981.36  199.95972.4391   204.4  971.58   222.8  971.22
  227.24972.4366   232.7  975.19   244.8  976.27   253.2   978.4   283.3  992.44
   324.9  997.99   357.3 1006.04   369.4 1008.14     406 1017.83   426.1 1026.52
#Mann= 3, -1 ,  0
       0     0.1       0  199.95   0.045       0  227.24     0.1       0
Bank Sta=199.95,227.24
XS Rating Curve= 0 ,0
Exp/Cntr(USF)=0,0
Exp/Cntr=0.3,0.1

Type RM Length L Ch R = 1 ,15295   ,276.9,286.3,284
XS GIS Cut Line= 5
1656424.45245719470142.8023273721656344.41647315470270.318611542
1656307.09233368470384.0871741341656290.13272194470457.144442723
 1656270.3460161470542.377868058
#Sta/Elev= 30
       0  1039.9     8.8 1035.38      22 1025.61    24.1 1024.74    68.5 1011.46
    95.2 1001.51   107.2   997.8   119.3  993.18   134.3     985   149.8  980.78
   156.8  977.46   170.6  972.46   177.5  971.33  206.36969.8491     219  968.44
  228.08969.8569   236.2  973.89   246.6  973.91   260.4   976.4   280.9  985.13
   317.9  993.28     328  997.53   344.9 1006.22   361.7 1009.75   371.8 1013.16
   381.9 1018.85   395.2  1031.1   408.8 1040.63   422.3 1046.26   432.8 1053.12
#Mann= 3, -1 ,  0
       0     0.1       0  206.36   0.045       0  228.08     0.1       0
#XS Ineff= 2 , 0
                          238.55          984.62
Permanent Ineff=
       F       F
Bank Sta=206.36,228.08
XS Rating Curve= 0 ,0
Exp/Cntr(USF)=0,0
Exp/Cntr=0.3,0.1

Type RM Length L Ch R = 1 ,15009   ,308.9,304.9,295.3
XS GIS Cut Line= 6
1656268.84973176469986.3572410941656210.60837843470051.657963499
1656160.68721843470107.6302925051656101.39009292470188.738726094
1656059.61753868470254.5427283351655999.93327484470326.623620927
#Sta/Elev= 30
       0  1051.8    34.5 1039.93    44.4 1034.67    61.3 1023.63    83.8 1015.81
   111.5  996.32   123.2  989.69   140.3  981.98   146.7   980.1   164.1  976.99
   184.7  975.29   196.4  970.79  211.08966.3349   218.3  964.95   229.8966.3354
   236.3  967.64   269.3  970.45   281.1  974.26   292.8  980.43   302.6  987.54
     312  995.58   330.1 1007.22   339.5 1010.51   352.4 1013.46   377.7 1022.29
   393.5 1034.03   411.7 1042.39   424.5 1045.16   428.8 1047.23   434.5  1052.3
#Mann= 3, -1 ,  0
       0     0.1       0  211.08   0.045       0   229.8     0.1       0
Bank Sta=211.08,229.8
XS Rating Curve= 0 ,0
Exp/Cntr(USF)=0,0
Exp/Cntr=0.3,0.1

Type RM Length L Ch R = 1 ,14704   ,254.4,255.8,253.1
XS GIS Cut Line= 6
1655887.41939226 469810.396963091655876.10150151469897.161881417
1655866.40040542469971.5318114161655853.46637617470070.691718087
1655847.60713592470146.1348086741655844.60287684470241.438423842
#Sta/Elev= 30
       0 1024.12    23.2 1016.49    56.3 1008.56    82.7   998.4   102.6   993.1
   119.1  982.78     129  978.34   158.8  978.77   162.1  977.44   168.7  972.53
   174.9  969.15   189.5  966.71  201.36962.1426   211.8  961.07  229.13962.1422
   234.9   963.6   245.1  963.36   261.4  964.73   271.3     970   288.4  975.64
   320.6  984.05   330.5  987.51   350.2  990.23   360.1  992.84   369.9  998.32
   379.8 1000.67   389.6 1006.32     406 1011.56   415.9 1012.68   433.5  1019.1
#Mann= 3, -1 ,  0
       0     0.1       0  201.36   0.045       0  229.13     0.1       0
Bank Sta=201.36,229.13
XS Rating Curve= 0 ,0
Exp/Cntr(USF)=0,0
Exp/Cntr=0.3,0.1

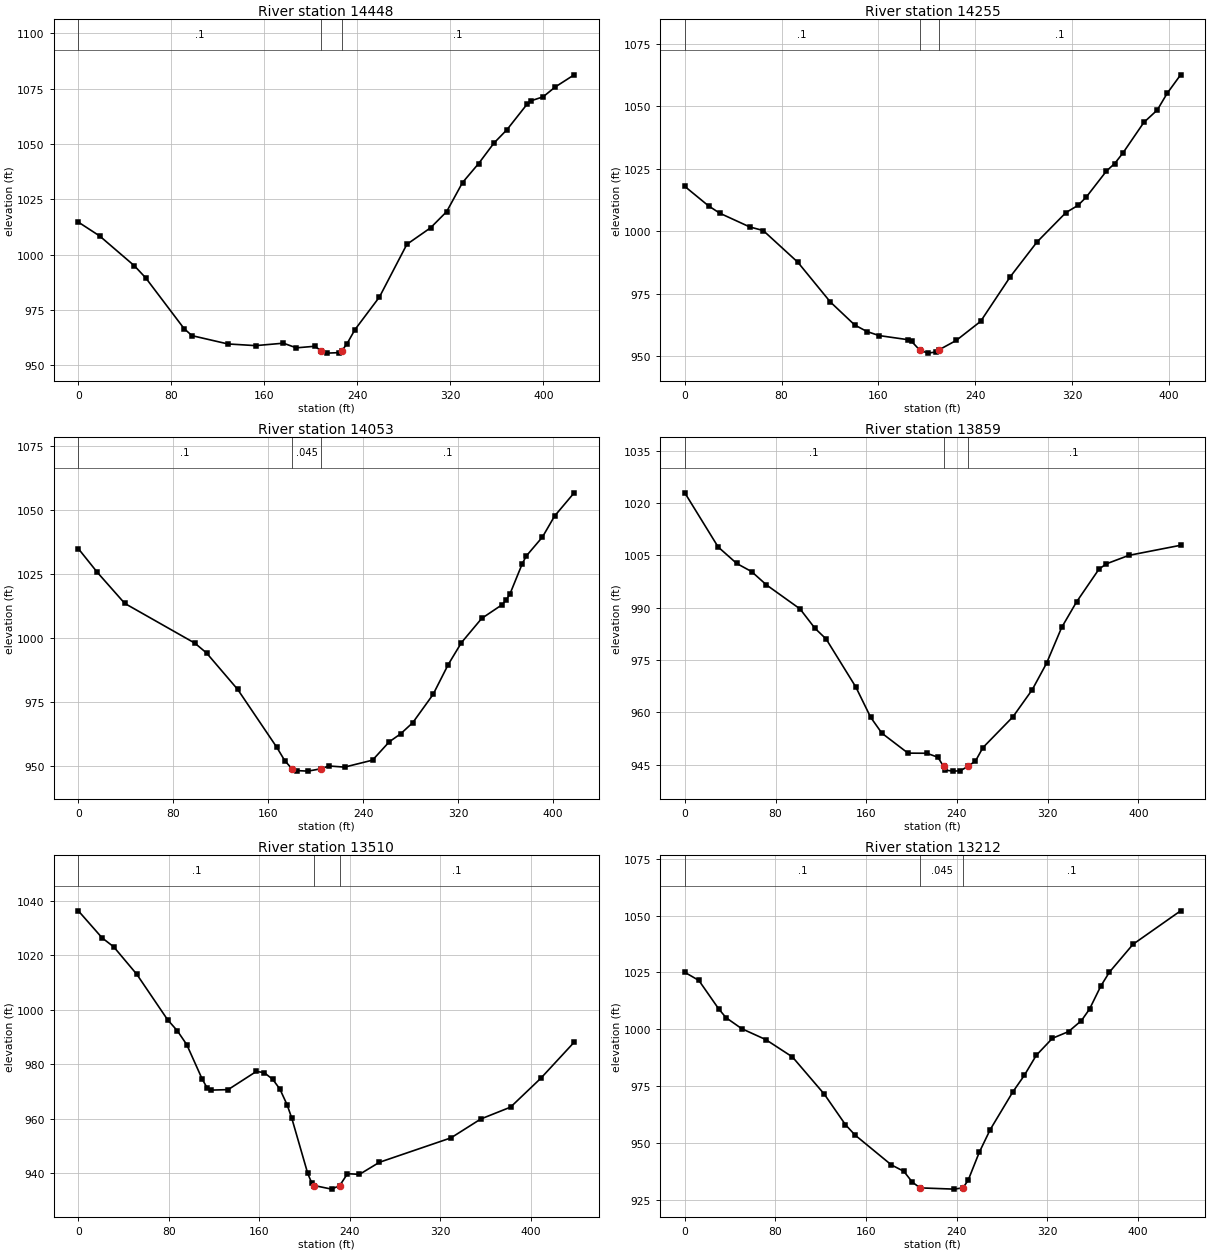
Type RM Length L Ch R = 1 ,14448   ,193.3,193.7,192
XS GIS Cut Line= 6
 1655660.1737669 469857.793161711655650.97266981469946.255255123
1655629.97303989470018.2554392121655601.97309589470114.255575289
1655579.92884864470185.9509699541655551.47254072470268.796932866
#Sta/Elev= 30
       0 1014.76    18.3 1008.51    48.2  995.03    57.9   989.6      91  966.61
    97.8  963.45   128.6  959.71   152.5  958.95   176.4  960.05   187.5  957.95
   203.7  958.67   208.7  956.54     214  955.56   224.2  955.78  226.53 956.533
   231.1  959.79   237.9  966.15     259  980.91   282.6 1004.72     303 1012.19
   316.8 1019.48   330.5 1032.65   344.3 1041.21   357.5 1050.47   368.8 1056.58
   385.9 1067.98   389.4 1069.58   399.8 1071.37   410.2 1075.81   426.5 1081.31
#Mann= 3, -1 ,  0
       0     0.1       0   208.7   0.045       0  226.53     0.1       0
Bank Sta=208.7,226.53
XS Rating Curve= 0 ,0
Exp/Cntr(USF)=0,0
Exp/Cntr=0.3,0.1

Type RM Length L Ch R = 1 ,14255   ,205.7,201.3,195.9
XS GIS Cut Line= 2
1655473.69796567469827.3430681571655387.11703688470227.881009754
#Sta/Elev= 30
       0 1017.93    19.6 1010.15    28.9 1007.21    53.7 1001.71    64.8 1000.28
    93.4   987.6   120.3  971.69   140.4   962.5   150.5  959.88   160.6  958.25
   184.1  956.63   187.4  955.95   194.1  952.48   200.8  951.23   207.6  951.68
  209.84952.4818   224.3  956.29   244.5  963.94     269  981.79   291.1  995.69
     315 1007.45     325 1010.35   331.8 1013.65   348.5 1024.08   355.3 1027.08
     362 1031.22   379.4 1043.53   390.5 1048.49   398.7 1055.19   409.8 1062.57
#Mann= 3, -1 ,  0
       0     0.1       0   194.1   0.045       0  209.84     0.1       0
Bank Sta=194.1,209.84
XS Rating Curve= 0 ,0
Exp/Cntr(USF)=0,0
Exp/Cntr=0.3,0.1

Type RM Length L Ch R = 1 ,14053   ,193.3,194.6,194.8
XS GIS Cut Line= 4
1655229.29679929469810.6768027711655226.09269269469973.802396297
1655247.13104921470067.6658331151655291.03870936 470219.92501542
#Sta/Elev= 30
       0  1034.9    16.1 1025.57    39.1 1013.49    98.2  997.94     108  994.12
   134.3  979.84   167.2  957.24   173.9  952.04   179.9948.8751     184  948.12
   193.5  947.91  204.86948.8685   210.9  949.93   224.3  949.48   247.9   952.2
     262  959.37   271.6   962.5   281.8  966.85   298.9  977.87   311.7  989.59
   322.8  998.14   339.9 1007.62     357 1012.95   360.4 1014.74   363.8 1017.29
     374 1028.92   377.4 1031.99   391.1 1039.45   401.3 1047.63   417.8 1056.72
#Mann= 3, -1 ,  0
       0     0.1       0   179.9   0.045       0  204.86     0.1       0
Bank Sta=179.9,204.86
XS Rating Curve= 0 ,0
Exp/Cntr(USF)=0,0
Exp/Cntr=0.3,0.1

Type RM Length L Ch R = 1 ,13859   ,344.9,349.3,343.2
XS GIS Cut Line= 3
1655043.59541924469830.2458188111655048.58891989470016.587278633
1655076.62656965470265.855824564
#Sta/Elev= 30
       0 1022.95    29.4 1007.43    45.8  1002.7    58.9 1000.38      72  996.56
   101.6  989.68   114.7  984.15   124.6  981.06   150.8   967.3   163.9  958.61
   173.8  954.06   196.8  948.35   213.4  948.31   223.2  947.17  228.16944.5335
   229.8  943.47   236.4  943.19     243  943.28   249.6  944.57   256.3  946.08
   262.9  949.94   289.3  958.74   306.3  966.49     319  974.11   332.3  984.36
   345.4  991.67   365.2 1001.08   371.8 1002.61   391.6 1005.03   437.2 1007.92
#Mann= 3, -1 ,  0
       0     0.1       0  228.16   0.045       0   249.6     0.1       0
Bank Sta=228.16,249.6
XS Rating Curve= 0 ,0
Exp/Cntr(USF)=0,0
Exp/Cntr=0.3,0.1

Type RM Length L Ch R = 1 ,13510   ,279.2,297.8,303.6
XS GIS Cut Line= 6
1654679.09536535469780.2306848321654702.64453085 469866.42441009
1654724.52211176469941.4482101651654762.50267884470039.120915085
1654773.02135859470115.0948445051654778.30185984470204.526752248
#Sta/Elev= 30
       0 1036.37    21.1  1026.4    31.3 1023.13    51.7 1013.04    78.9  996.36
    87.5   992.3    95.9  987.19   109.6  974.47     114  971.22   117.3  970.45
   132.5  970.63   157.4   977.3   164.3  976.92     172   974.4   178.3  970.83
   184.7  965.03   188.8  960.15   202.9  939.85   206.4  936.35   208.9  935.35
     224  934.05  231.21935.3528   238.1  939.72   248.7  939.48   266.3  943.91
   329.6  952.89     356  959.83   382.3  964.19   409.1  974.81   438.6  988.06
#Mann= 3, -1 ,  0
       0     0.1       0   208.9   0.045       0  231.21     0.1       0
Bank Sta=208.9,231.21
XS Rating Curve= 0 ,0
Exp/Cntr(USF)=0,0
Exp/Cntr=0.3,0.1

Type RM Length L Ch R = 1 ,13212   ,310.1,305,279.1
XS GIS Cut Line= 6
1654589.47841859469773.8852250871654536.82957375469851.076999843
1654487.51832068469914.2507580071654441.02202259470004.337191999
1654411.99320926470073.4915812611654378.12615101 470154.17153801
#Sta/Elev= 30
       0 1025.05    12.4 1021.49    29.8 1009.06    36.3 1005.15    50.2 1000.29
    71.4   995.5      95  987.85   123.1   971.5   141.7  958.14   150.1  953.59
   182.2  940.45   193.3  937.59   200.7  932.88  207.57930.3283   237.6  929.78
  245.43930.3275     250  933.65   259.8  945.92   269.5  955.95   289.4  972.47
   299.6  979.78   310.1  988.56   324.4  996.07   338.6     999     350 1003.85
   357.1 1008.87   367.1 1019.03   374.6 1025.09   395.5 1037.37   437.5 1052.07
#Mann= 3, -1 ,  0
       0     0.1       0  207.57   0.045       0  245.43     0.1       0
Bank Sta=207.57,245.43
XS Rating Curve= 0 ,0
Exp/Cntr(USF)=0,0
Exp/Cntr=0.3,0.1

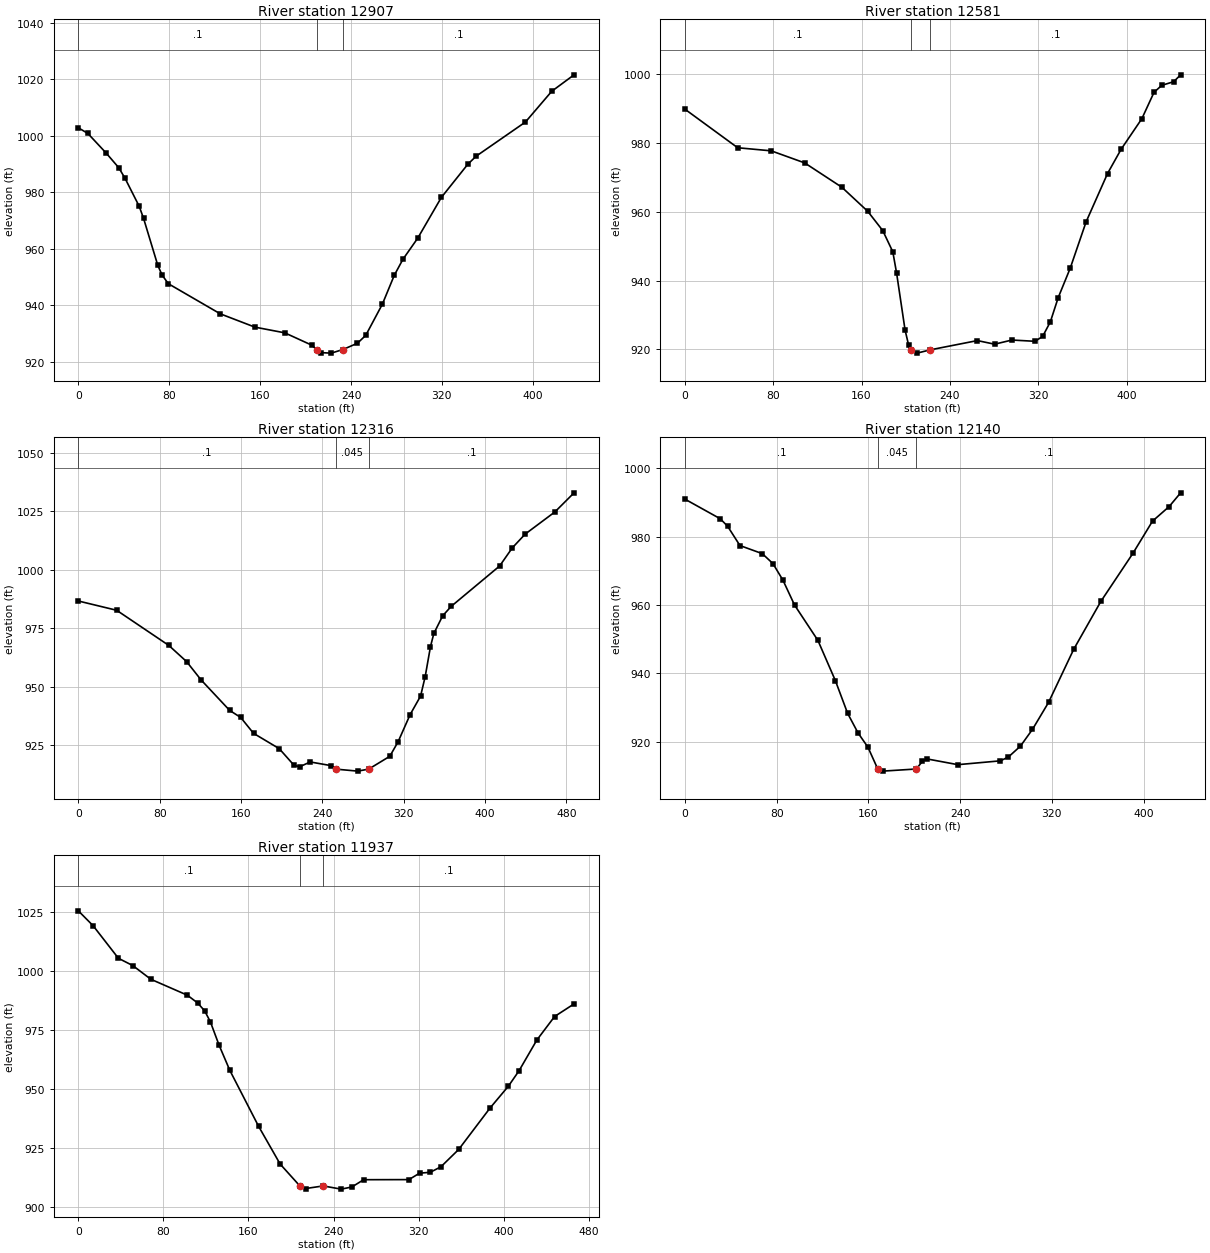
Type RM Length L Ch R = 1 ,12907   ,325.4,325.8,320.9
XS GIS Cut Line= 6
1654108.35339659469744.7038530111654163.13576734469817.400229916
1654214.37877509469875.557265833  1654258.240564469965.771324262
1654281.76249859470037.6084509191654296.46916209470128.276248589
#Sta/Elev= 30
       0 1002.86     8.3  1000.9    24.7  993.84    35.6  988.73      41  985.08
    53.5  975.15    57.4  970.84    69.9  954.24    73.7  950.78    79.2   947.7
   124.9  937.04   155.4  932.33   181.7  930.31   205.5  925.94   209.7924.4006
   213.6   923.3   222.6  923.13  232.88924.4033   245.7  926.64     253  929.44
   267.6  940.46   278.1  950.69   285.7  956.34   298.7   963.8   319.5  978.22
   342.9  990.02   350.2  992.84   393.5  1004.9   416.7  1015.8   436.3 1021.61
#Mann= 3, -1 ,  0
       0     0.1       0   209.7   0.045       0  232.88     0.1       0
Bank Sta=209.7,232.88
XS Rating Curve= 0 ,0
Exp/Cntr(USF)=0,0
Exp/Cntr=0.3,0.1

Type RM Length L Ch R = 1 ,12581   ,240.4,265.1,281.8
XS GIS Cut Line= 4
1653963.92663737469793.3581251241653921.56093108469974.570744673
1654023.53472444 470083.040288871654070.63428644 470186.89747072
#Sta/Elev= 30
       0  989.87    47.8  978.65    78.2  977.75   108.5  974.24   142.2  967.15
   165.6  960.16   179.2  954.55   188.3  948.39   191.7  942.27   199.4  925.65
   202.7  921.14  204.95919.8444   210.3  918.91     222  919.85   264.9  922.56
   280.5  921.51   296.2  922.72   317.1  922.35     324  923.76     331  928.01
   338.1  935.04     349  943.62   363.4  957.11   382.8  971.15   395.1  978.21
   413.9  987.11   424.9  994.77   431.9   996.8   442.7  997.86     449  999.86
#Mann= 3, -1 ,  0
       0     0.1       0  204.95   0.045       0     222     0.1       0
Bank Sta=204.95,222
XS Rating Curve= 0 ,0
Exp/Cntr(USF)=0,0
Exp/Cntr=0.3,0.1

Type RM Length L Ch R = 1 ,12316   ,175.1,176,178.6
XS GIS Cut Line= 6
1653881.54413892469779.4846233431653841.31948183469887.391887844
1653802.04593834  469986.36675551653730.89089692470056.674357668
1653673.35426658470106.8747165951653603.17166418 470162.38772893
#Sta/Elev= 30
       0  986.64    37.7  982.67      89  967.62   106.5  960.69   120.6  952.92
   148.8  939.82   159.7  936.78   172.3     930   197.6  923.43   212.3  916.23
   217.8  915.71     228  917.75   248.3  916.19  253.27914.6765   274.7  913.82
  285.53 914.675   306.3  920.17   314.4  926.33   326.3  938.02   336.6  945.97
   341.1  954.28   346.3   967.1   349.6  972.74   358.3   980.3   366.7  984.35
   414.3 1001.62   426.8  1009.4   439.4 1015.26   468.7 1024.78   487.5 1032.94
#Mann= 3, -1 ,  0
       0     0.1       0  253.27   0.045       0  285.53     0.1       0
Bank Sta=253.27,285.53
XS Rating Curve= 0 ,0
Exp/Cntr(USF)=0,0
Exp/Cntr=0.3,0.1

Type RM Length L Ch R = 1 ,12140   ,203.4,202.8,177
XS GIS Cut Line= 3
1653844.87904166469745.4271697421653640.77947164 469917.80413479
1653582.70875262470072.353520182
#Sta/Elev= 30
       0  990.97    30.8  985.23    37.2  983.06      48  977.39    67.5  975.02
    76.8   972.1    85.5  967.26    95.6     960     116  949.64   131.2   937.9
   141.9  928.32     151  922.58   159.6  918.43   168.2  912.02   172.5  911.42
  201.77 912.044   207.1  914.27   211.1  914.99     238  913.31   275.1  914.43
   282.1  915.55   292.6  918.73   303.1  923.63   317.1   931.5     339  947.01
   362.7  961.04   390.7  975.12   407.8  984.54   422.3   988.8   432.3  992.81
#Mann= 3, -1 ,  0
       0     0.1       0   168.2   0.045       0  201.77     0.1       0
Bank Sta=168.2,201.77
XS Rating Curve= 0 ,0
Exp/Cntr(USF)=0,0
Exp/Cntr=0.3,0.1

Type RM Length L Ch R = 1 ,11937   ,222,223.8,219.7
XS GIS Cut Line= 4
 1653506.5484089469600.0882955071653528.86923041469685.283663171
 1653572.8136853469867.2362984841653536.80157825470054.802376892
#Sta/Elev= 30
       0 1025.36    13.9 1019.06    37.7 1005.27    51.2 1002.19    68.2  996.39
   102.5  989.65   112.2  986.36   118.8  983.02   124.2  978.36   132.4  968.45
   142.5   957.8   169.5  934.17   189.8  918.16   208.5  908.82   213.9  907.81
   230.3   908.9   247.2  907.55   257.3  908.46   268.3  911.54   310.9  911.58
   320.9   914.3     331  914.68     341  917.01   357.7  924.34   387.1  941.83
   404.5  951.16   414.5  957.69   431.2  970.66   447.9  980.62   466.2  985.96
#Mann= 3, -1 ,  0
       0     0.1       0   208.5   0.045       0   230.3     0.1       0
Bank Sta=208.5,230.3
XS Rating Curve= 0 ,0
Exp/Cntr(USF)=0,0
Exp/Cntr=0.3,0.1