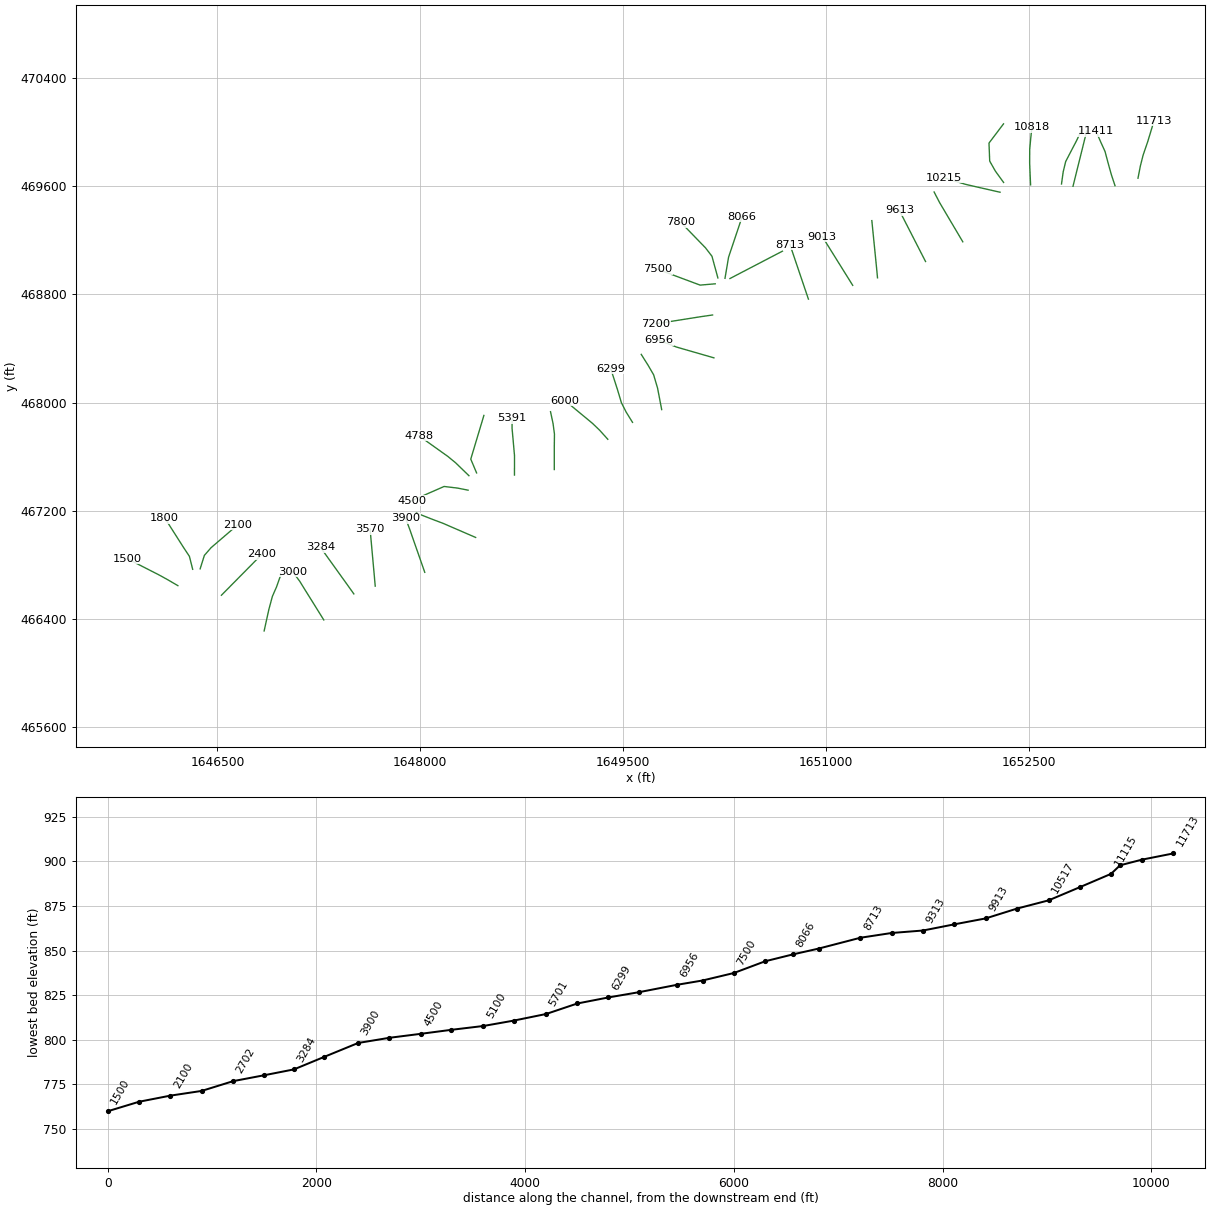
HEC-RAS study MagtyRn.prj: MagtyRn

--- MagtyRn.g01 (geometry) --- (continued)

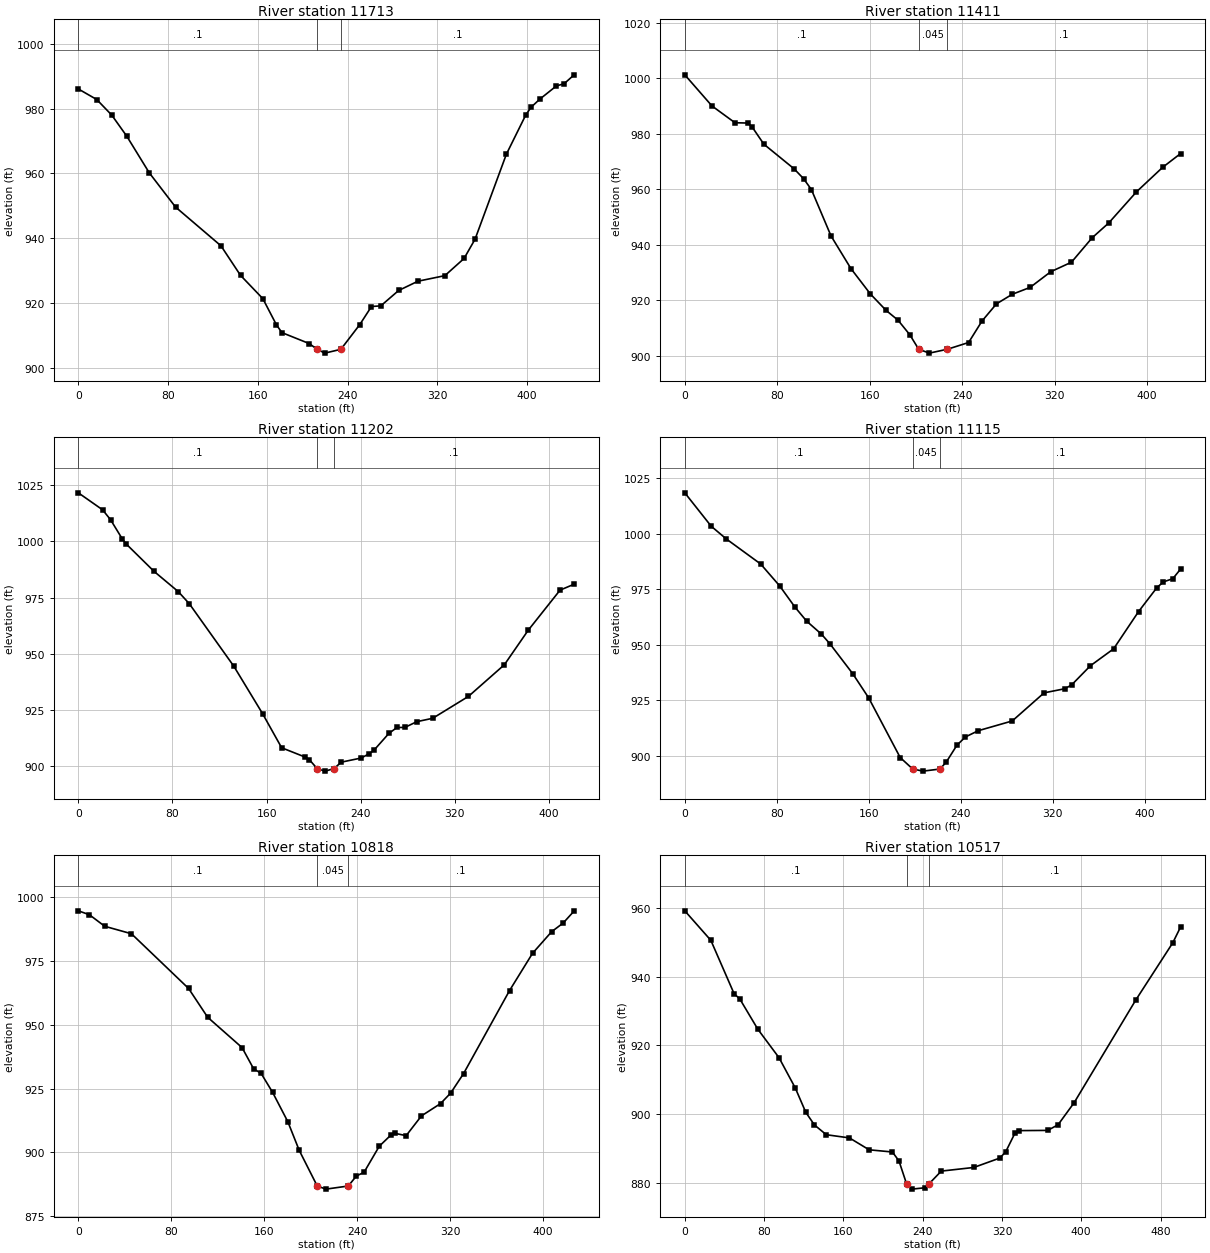
Type RM Length L Ch R = 1 ,11713   ,291.3,302.1,304.3
XS GIS Cut Line= 6
1653305.36550125469659.7850595861653323.28114784469751.437763423
1653343.34803684469830.8844549211653377.12060709469929.256633505
1653398.88237458470000.9950070831653424.26880676470084.685784593
#Sta/Elev= 30
       0  986.12    16.4  982.86    29.8  978.03    43.2   971.5    63.2   960.2
    86.6  949.62   127.1  937.63   144.5  928.51   164.4   921.3   176.5  913.22
   181.4   910.8   205.7  907.42  212.88905.6288   219.6  904.46  233.93905.6384
   250.8  913.29   261.2  918.87   269.5  919.07   285.4  923.82   302.6  926.69
   326.6  928.41   343.7  933.72   353.5  939.68   381.4  965.95   398.6  978.02
   403.4  980.47   411.3     983     426  987.07   432.8  987.73   441.8  990.49
#Mann= 3, -1 ,  0
       0     0.1       0  212.88   0.045       0  233.93     0.1       0
Bank Sta=212.88,233.93
XS Rating Curve= 0 ,0
Exp/Cntr(USF)=0,0
Exp/Cntr=0.3,0.1

Type RM Length L Ch R = 1 ,11411   ,213,209.7,203.2
XS GIS Cut Line= 6
1653135.44490933469604.4091860951653107.90132926469687.969386429
1653087.63857451469760.4830209171653061.83285184469857.414257512
1653030.18298076469926.8130688371652994.99079393470008.658377588
#Sta/Elev= 30
       0 1001.32    23.5   990.1    43.4  984.04    54.5  983.93      58  982.67
    68.4   976.3    94.5  967.44   102.7  963.89   109.5  959.95   126.5  943.21
   143.7  931.45   160.6  922.26   174.2  916.34   184.4  912.86   194.6  907.61
   202.3  902.38   211.5  900.96  227.24902.3683   245.5  904.79   257.1  912.54
   269.6  918.73   283.3  922.19   298.7  924.66   316.5   930.3   334.5  933.76
   352.4  942.57   366.7  947.89   390.7  959.12   413.3  967.94   428.9  972.94
#Mann= 3, -1 ,  0
       0     0.1       0   202.3   0.045       0  227.24     0.1       0
Bank Sta=202.3,227.24
XS Rating Curve= 0 ,0
Exp/Cntr(USF)=0,0
Exp/Cntr=0.3,0.1

Type RM Length L Ch R = 1 ,11202   ,91.5,86.2,85.2
XS GIS Cut Line= 2
1652824.90444583469600.1001739061652926.49543283470009.085824818
#Sta/Elev= 30
       0 1021.56    20.6 1014.01    27.4 1009.59    37.5 1000.94    40.9   998.7
    64.3  986.65    84.9  977.64    94.3  972.25   132.2   944.4   156.6  923.34
   172.8  908.18     193  903.99   196.4  902.85   203.2  898.77   209.9  897.79
  217.25  898.92   223.5  901.78   240.4  903.62   247.1  905.49   251.4  907.17
     264  914.59   270.8   917.2   277.5  917.22   287.7  919.79   301.2  921.29
   331.6  931.05   362.1  945.11   382.3  960.41   409.4  978.28   421.4  980.93
#Mann= 3, -1 ,  0
       0     0.1       0   203.2   0.045       0  217.25     0.1       0
Bank Sta=203.2,217.25
XS Rating Curve= 0 ,0
Exp/Cntr(USF)=0,0
Exp/Cntr=0.3,0.1

Type RM Length L Ch R = 1 ,11115   ,285.4,297.8,297.1
XS GIS Cut Line= 6
1652740.01984717469617.0571266711652752.51686943469707.211145833
1652770.76092742469782.838947341  1652816.790691469871.616328835
1652851.59180251469938.0535319151652888.47821167470017.509409755
#Sta/Elev= 30
       0 1018.48      23 1003.41    36.2  997.65      66  986.39    82.6  976.48
    95.9  966.92     106  960.64   118.9  954.76   126.3  950.39   146.1  936.95
     160  926.03   187.4  899.15  198.28893.9621   207.3  893.01  222.04893.9596
   227.5   897.1   236.8  904.72   244.2  908.43   255.3  911.23   284.9  915.63
   312.6   928.3   330.9  930.19   336.7  931.95   352.9  940.52   373.1  948.15
   394.8  964.94   410.8  975.77   416.5  978.34   424.6  979.77   431.4  984.13
#Mann= 3, -1 ,  0
       0     0.1       0  198.28   0.045       0  222.04     0.1       0
Bank Sta=198.28,222.04
XS Rating Curve= 0 ,0
Exp/Cntr(USF)=0,0
Exp/Cntr=0.3,0.1

Type RM Length L Ch R = 1 ,10818   ,299.3,300.3,300.4
XS GIS Cut Line= 6
1652511.40416268469610.5817459231652507.65417017469698.000534341
1652504.43993776  469772.93017451652504.99243009469873.043491334
1652511.95468651469948.4140755091652521.07573126470036.386996672
#Sta/Elev= 30
       0  994.74     9.5  993.22    22.7  988.68    45.7  985.75    94.9  964.28
   111.3  952.99   140.9  941.09   150.8  932.81   157.3  930.97   167.2  923.52
   180.3  912.01   190.1  900.77  205.59886.7941   213.1  885.57  232.32 886.794
   239.3  890.72   245.9  892.18     259  902.41   268.9  906.74   272.2  907.49
   282.1  906.54   295.3  914.31   311.7  919.12   320.4  923.24   331.5  930.87
   371.1  963.47   390.9  978.09   407.4  986.59   417.2  989.93   426.7  994.69
#Mann= 3, -1 ,  0
       0     0.1       0  205.59   0.045       0  232.32     0.1       0
Bank Sta=205.59,232.32
XS Rating Curve= 0 ,0
Exp/Cntr(USF)=0,0
Exp/Cntr=0.3,0.1

Type RM Length L Ch R = 1 ,10517   ,282.7,302,314.1
XS GIS Cut Line= 5
1652311.85994235469628.3628783381652250.85809584 469712.68456009
1652209.18790358469786.3350033461652203.90871467469919.663090195
1652311.38424502 470061.79666763
#Sta/Elev= 30
       0   959.2    26.3   950.6    49.8  935.03    55.4  933.59    73.7  924.72
    95.1  916.42   111.5   907.6   122.1  900.52   130.8  896.85   142.8     894
   166.1  893.08     186  889.61   209.5  888.97   216.1  886.37223.7669879.6982
   229.2  878.16   242.3  878.56246.6349879.7653   258.8  883.41   291.6  884.47
   317.9  887.21   323.8  889.03     333  894.39   337.3   895.2   366.1  895.26
   376.6  896.89   392.9  903.35   454.9  933.16   492.4   949.9   500.3  954.52
#Mann= 3, -1 ,  0
       0     0.1       0223.7669   0.045       0246.6349     0.1       0
Bank Sta=223.7669,246.6349
XS Rating Curve= 0 ,0
Exp/Cntr(USF)=0,0
Exp/Cntr=0.3,0.1

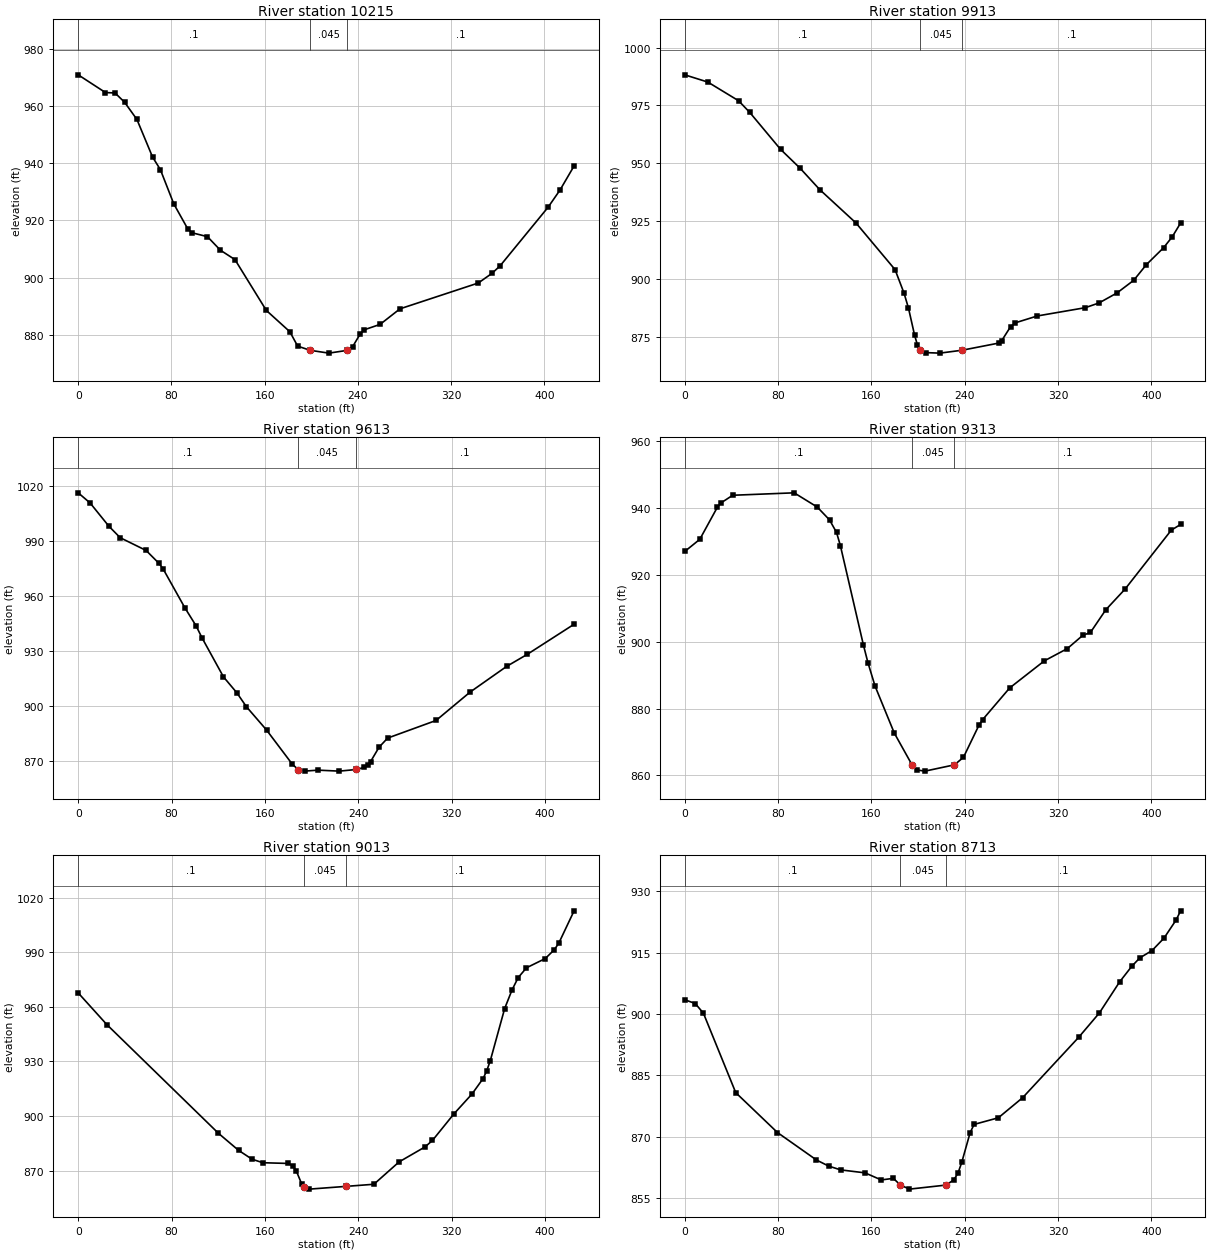
Type RM Length L Ch R = 1 ,10215   ,308.7,302.1,280.9
XS GIS Cut Line= 6
1652285.84982376469556.0070519151652200.52584742469575.399073511
 1652127.3908231469592.0207594191652029.96877384469614.584362596
1651957.95448217469636.1364848321651874.26567318469662.723701999
#Sta/Elev= 30
       0  970.88    23.4  964.68    31.6  964.54    39.8  961.29    50.4  955.26
    63.8  942.13    70.5  937.74      82  925.77    94.1  916.94    97.5  915.67
   110.9  914.29     122  909.56   134.5  906.27   161.4  888.51   181.6  881.05
   188.3  876.02  199.09874.5481   215.1  873.57  231.06874.5477   235.5  875.84
   242.2  880.43   245.6  881.76     259  883.61   276.1  889.06   343.3  898.09
     355  901.45   361.9  904.04   403.2  924.59   413.5  930.65   425.5  939.03
#Mann= 3, -1 ,  0
       0     0.1       0  199.09   0.045       0  231.06     0.1       0
Bank Sta=199.09,231.06
XS Rating Curve= 0 ,0
Exp/Cntr(USF)=0,0
Exp/Cntr=0.3,0.1

Type RM Length L Ch R = 1 ,9913    ,301.1,300,298.1
XS GIS Cut Line= 6
1652010.24604426469189.2781265831651965.73268184469264.609340757
1651927.57823059469329.1787654161651876.70562892469415.271769091
1651838.55150576469479.8415218441651798.29633692469557.689135179
#Sta/Elev= 30
       0  988.23    19.8   985.1    46.2  977.02    55.8  971.96    82.1  956.07
    98.9  947.89   115.7  938.67   146.8  924.24   180.3  904.09     188  893.92
   191.8  887.48   197.1  875.65   199.5  871.53  202.06869.2914   206.7  868.25
   218.7  868.03  237.86869.2893     269  872.35   271.8  873.48   279.4  879.52
   283.5  881.14   302.3  884.09   343.3  887.65   355.1  889.69   370.6  894.03
   384.9  899.49   395.7  906.22   410.5  913.56   417.9  918.25   425.1  924.24
#Mann= 3, -1 ,  0
       0     0.1       0  202.06   0.045       0  237.86     0.1       0
Bank Sta=202.06,237.86
XS Rating Curve= 0 ,0
Exp/Cntr(USF)=0,0
Exp/Cntr=0.3,0.1

Type RM Length L Ch R = 1 ,9613    ,307.1,300,291.8
XS GIS Cut Line= 6
1651734.87290734469043.4299930931651694.98387951469121.309102416
1651660.79333109 469188.062249751651615.20615192469277.066664919
1651581.01527542469343.8201403321651541.12657568469421.698921591
#Sta/Elev= 30
       0 1016.25    10.2 1010.72    26.3  998.06      36  991.81    58.2  984.87
    69.2  977.86    72.7   974.9    91.3  953.78     101  943.86   106.1   937.3
   124.5  916.04     136  907.34   144.1  899.83   161.4  887.11   183.5  868.49
  188.48865.6053   194.5  864.75   205.6  865.25   223.8  864.72  238.37865.6066
   244.9  866.73   248.2  868.17   250.6  869.94   257.9  877.79   265.2  882.71
   306.7  892.31   335.9  907.77   367.2  921.75   384.7  928.24     425   944.7
#Mann= 3, -1 ,  0
       0     0.1       0  188.48   0.045       0  238.37     0.1       0
Bank Sta=188.48,238.37
XS Rating Curve= 0 ,0
Exp/Cntr(USF)=0,0
Exp/Cntr=0.3,0.1

Type RM Length L Ch R = 1 ,9313    ,290.5,300,307.1
XS GIS Cut Line= 6
1651379.84408984468923.035548836 1651371.5160225469010.139377251
1651364.05343901469084.767180756 1651354.1029996469184.270918757
1651346.64008801469258.8987222611651337.93341251469345.964493006
#Sta/Elev= 30
       0  927.05    12.9  930.69    27.9  940.26    30.9  941.56    41.1  943.89
    93.8  944.62   113.6  940.35   124.1  936.51   130.1  932.75   133.4   928.8
   153.2  898.94     157  893.76   163.1  886.74   179.6  872.66  194.79863.1468
   199.4  861.59   205.9  861.26   231.2863.1489   238.9  865.41   252.1  874.97
   255.4  876.72   278.5  886.18   308.2  894.29   327.9  897.96   341.1  901.92
   347.7  902.79   360.9   909.6   377.4  915.79     417  933.44     425  935.15
#Mann= 3, -1 ,  0
       0     0.1       0  194.79   0.045       0   231.2     0.1       0
Bank Sta=194.79,231.2
XS Rating Curve= 0 ,0
Exp/Cntr(USF)=0,0
Exp/Cntr=0.3,0.1

Type RM Length L Ch R = 1 ,9013    ,303.1,300,295.3
XS GIS Cut Line= 6
1651196.54294726468867.0625636731651150.25498208468941.316352174
1651110.57986459469004.9628784211651057.67905176469089.824913427
1651018.00393426469153.4711115961650971.71564101469227.725228176
#Sta/Elev= 30
       0  967.65    24.5  950.28   120.2  890.54   137.4   881.2     149   876.3
   158.3  874.38   179.8  873.99   183.8   872.8   186.9  869.88   191.5  862.79
  193.23861.3013   198.1  859.88   229.1  861.37   253.4  862.55     275  874.83
   297.3  883.09   303.6  886.62   322.1  901.28   337.5  912.13     347  920.61
     350  924.68   353.2  930.47   365.5  959.08   371.8  969.28   377.1  976.08
   384.2  981.45   400.3  986.53     408  991.34   411.9     995     425 1012.74
#Mann= 3, -1 ,  0
       0     0.1       0  193.23   0.045       0   229.1     0.1       0
Bank Sta=193.23,229.1
XS Rating Curve= 0 ,0
Exp/Cntr(USF)=0,0
Exp/Cntr=0.3,0.1

Type RM Length L Ch R = 1 ,8713    ,428.2,401.2,375.9
XS GIS Cut Line= 6
1650869.05213243468765.1152610031650841.00002317468847.996656924
1650816.95512375 468919.03785342 1650784.8951485469013.759448752
1650760.85057718469084.8006452621650732.79813984469167.682041168
#Sta/Elev= 30
       0  903.51       9  902.58      16  900.22    43.7   880.8    79.5  871.04
   112.9  864.33   123.3  862.85   133.7  861.91   154.5  861.19   168.4  859.46
   178.8  859.84  184.86858.1981   192.6  857.21  223.93858.1995   230.7  859.49
   234.2  861.13   237.4  863.74   244.6  871.02     248  873.03   268.8  874.65
   289.6  879.56   337.5  894.28   355.4  900.29   372.7  907.86   383.1  911.67
     390  913.73   400.5  915.53   410.8  918.58   421.1  922.99     425  925.24
#Mann= 3, -1 ,  0
       0     0.1       0  184.86   0.045       0  223.93     0.1       0
Bank Sta=184.86,223.93
XS Rating Curve= 0 ,0
Exp/Cntr(USF)=0,0
Exp/Cntr=0.3,0.1

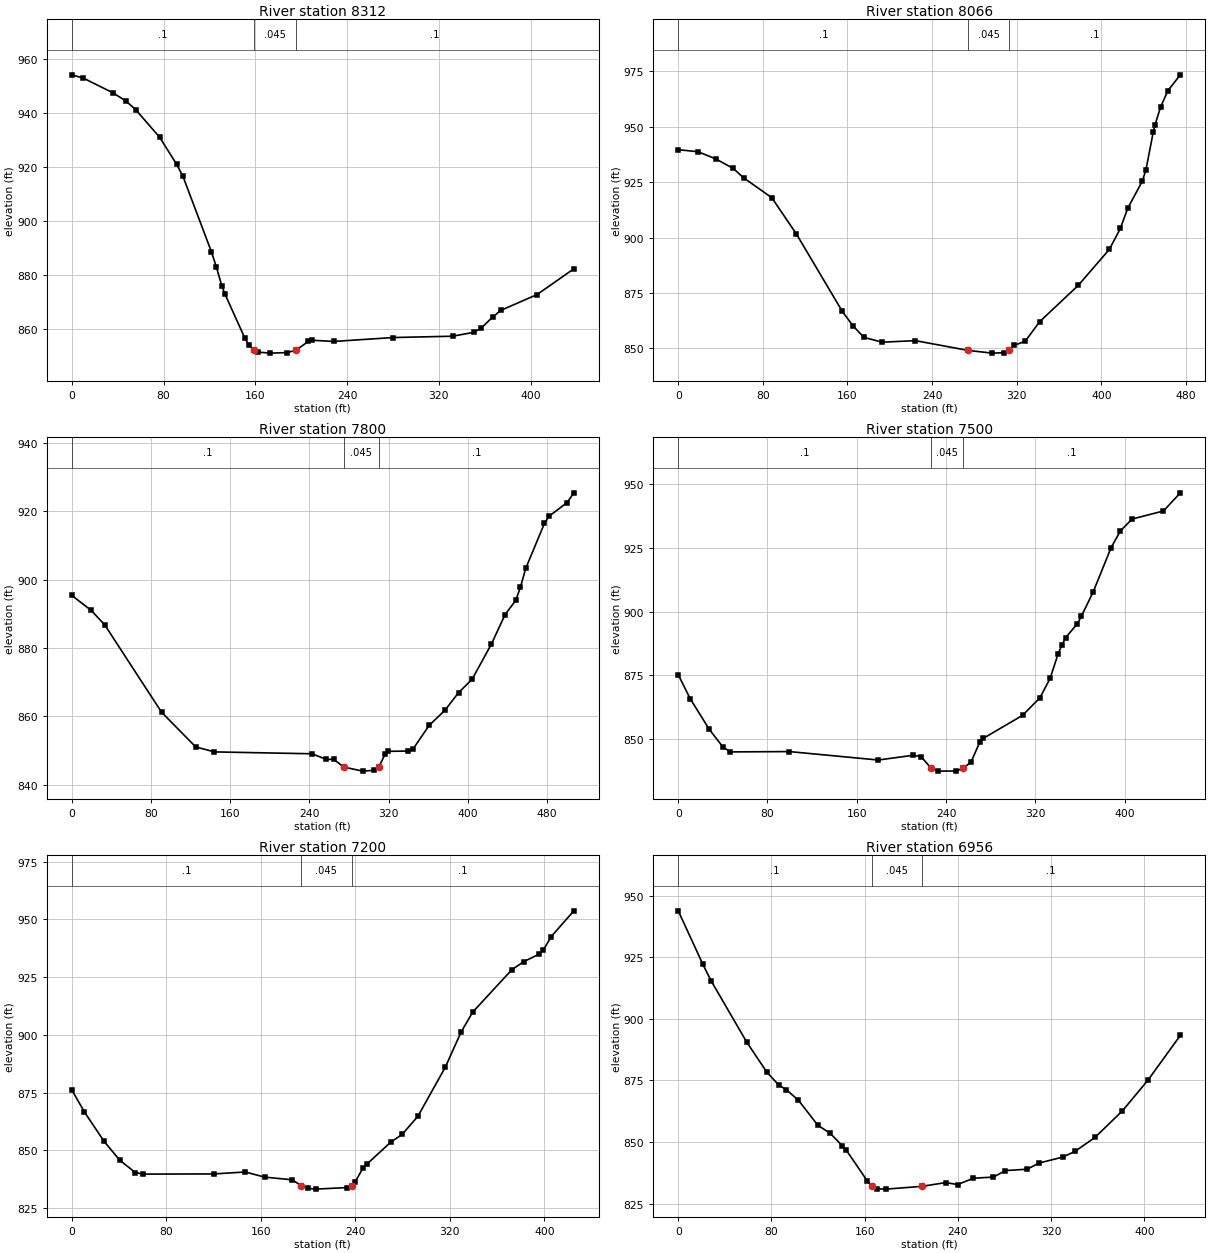
Type RM Length L Ch R = 1 ,8312    ,226.4,245.6,254.6
XS GIS Cut Line= 2
 1650288.9468569468917.5442488641650676.96663265469119.908359521
#Sta/Elev= 30
       0  954.12      10  952.92    35.9  947.46      47  944.48    55.6  941.28
    76.6     931    91.4  921.01    96.9  916.55   121.7  888.65   126.1  882.89
   130.9  875.86   133.4  873.08   150.6   856.9   154.3  854.08  159.18852.2437
   162.6  851.48   172.8  851.12   187.6  851.31   195.5852.2181   206.3   855.5
   209.8  855.88   228.2  855.44   280.1  856.89   331.9  857.38   350.4  858.83
   357.1  860.46   366.8  864.47   374.1  866.97   405.5  872.79   437.6  882.32
#Mann= 3, -1 ,  0
       0     0.1       0  159.18   0.045       0   195.5     0.1       0
Bank Sta=159.18,195.5
XS Rating Curve= 0 ,0
Exp/Cntr(USF)=0,0
Exp/Cntr=0.3,0.1

Type RM Length L Ch R = 1 ,8066    ,241.3,266.4,281.5
XS GIS Cut Line= 3
1650252.37718467468919.2990077591650278.72242357469075.359432821
1650379.34944454469375.355686973
#Sta/Elev= 30
       0  939.65    18.7  938.72    35.3  935.54    51.9  931.22    61.9  926.94
    88.5  917.97   111.8  901.56   155.1  866.72   165.3  860.14   175.7  854.94
     193  852.82   224.2  853.51  274.23 849.094   296.8  847.88   308.2  848.07
  312.44849.1484   317.6  851.38     328  853.23   341.8  862.09   378.2  878.44
   407.6  894.68     418   904.1     425  913.24   438.7  925.39   442.2  930.54
   449.1   947.6   450.7  950.71     456  958.81   462.9  966.24   474.7  973.42
#Mann= 3, -1 ,  0
       0     0.1       0  274.23   0.045       0  312.44     0.1       0
Bank Sta=274.23,312.44
XS Rating Curve= 0 ,0
Exp/Cntr(USF)=0,0
Exp/Cntr=0.3,0.1

Type RM Length L Ch R = 1 ,7800    ,290.8,300,306.2
XS GIS Cut Line= 6
1650199.82906142468921.958123177 1650155.9948315469082.398091003
1650108.27937576469144.6348431711650038.64762525469216.407993585
 1649986.4243045469270.2385945921649925.49693292469333.040962428
#Sta/Elev= 30
       0  895.37    19.7  890.97    33.3  886.76    90.7  861.24   125.2   851.1
   144.1  849.64   242.8  849.09   256.7  847.48   264.7  847.45  274.79845.2078
   293.9  844.02   305.5  844.26  310.12 845.209   316.5  848.95   319.4  849.81
   340.1  849.88   344.9  850.55   361.1   857.4     377  861.81   390.7  866.94
   404.4  870.85   423.8  881.08   437.7  889.74   448.5  893.93   453.2  897.71
   458.6  903.27   477.5  916.42   482.1  918.49   500.4   922.5   507.2  925.34
#Mann= 3, -1 ,  0
       0     0.1       0  274.79   0.045       0  310.12     0.1       0
Bank Sta=274.79,310.12
XS Rating Curve= 0 ,0
Exp/Cntr(USF)=0,0
Exp/Cntr=0.3,0.1

Type RM Length L Ch R = 1 ,7500    ,293.4,300,309.4
XS GIS Cut Line= 6
1650180.39414118468878.4913457611650068.28601742 468868.92837359
1649998.02270651468895.1592922511649904.33851068468930.134287924
1649834.07519975468956.3655346781649752.10161042468986.968819916
#Sta/Elev= 30
       0  875.28    10.6  865.93    27.8  853.85    40.2  846.81    46.8  844.98
    99.5  845.11   179.2   841.8   210.7  843.66   217.7  843.12226.8373838.4906
   232.4  837.44   249.3  837.49254.8273838.4771   262.3  840.88   270.3  848.84
   273.2  850.25   308.6  859.32   324.2  866.23   333.3  873.84   340.3   883.2
   343.8  886.86   347.3  889.86   357.8  895.31   361.3  898.17   371.8  907.64
   387.9  925.04   396.3   931.7   406.8  936.34   434.9   939.5     450  946.62
#Mann= 3, -1 ,  0
       0     0.1       0226.8373   0.045       0254.8273     0.1       0
Bank Sta=226.8373,254.8273
XS Rating Curve= 0 ,0
Exp/Cntr(USF)=0,0
Exp/Cntr=0.3,0.1

Type RM Length L Ch R = 1 ,7200    ,248.2,244.3,228.8
XS GIS Cut Line= 6
1650160.76286659468647.9137237521650074.15608442468635.388486341
1650000.07782051468623.6663969161649901.30669259468608.037819251
1649827.22842868468596.3163859991649740.80340467468582.641216502
#Sta/Elev= 30
       0  876.23    10.7  866.66    27.3  853.96    40.6  845.77    53.8  840.43
    60.4  839.75   120.2  839.83   146.8  840.66   163.4  838.44   186.6  837.29
  194.16834.7637   199.9  833.56   206.5  833.25   233.1  833.93   236.8834.7609
   239.8  836.35   246.4  842.24   249.7  844.02   270.1  853.62   279.6   856.9
   292.9  864.71   316.2  886.03   329.4  901.07   339.4  909.89   372.6  928.26
   382.6  931.71   395.9  935.02   399.2  936.75   405.8  942.52     425  953.71
#Mann= 3, -1 ,  0
       0     0.1       0  194.16   0.045       0   236.8     0.1       0
Bank Sta=194.16,236.8
XS Rating Curve= 0 ,0
Exp/Cntr(USF)=0,0
Exp/Cntr=0.3,0.1

Type RM Length L Ch R = 1 ,6956    ,375.9,360.7,338
XS GIS Cut Line= 3
1650170.55737802468330.7771585731649894.83083372468410.362545696
1649760.58059609468462.215604335
#Sta/Elev= 30
       0  943.81    21.2  922.04    28.1  915.49    58.8  890.51    75.9  878.42
    86.1  873.17    92.9  871.16   103.2   866.9   119.8  856.79   130.5  853.46
   140.8  848.45   144.2  846.69   162.2  834.22  166.19  831.97   170.2     831
   178.3  830.85     209  831.97   229.5   833.5   239.8  832.71   253.4  835.28
   270.5  835.74   280.8  838.37   299.5  838.94   309.6  841.43   329.8  843.83
   340.4  846.13   357.8  851.89   381.2  862.62     403     875   430.9  893.23
#Mann= 3, -1 ,  0
       0     0.1       0  166.19   0.045       0     209     0.1       0
Bank Sta=166.19,209
XS Rating Curve= 0 ,0
Exp/Cntr(USF)=0,0
Exp/Cntr=0.3,0.1

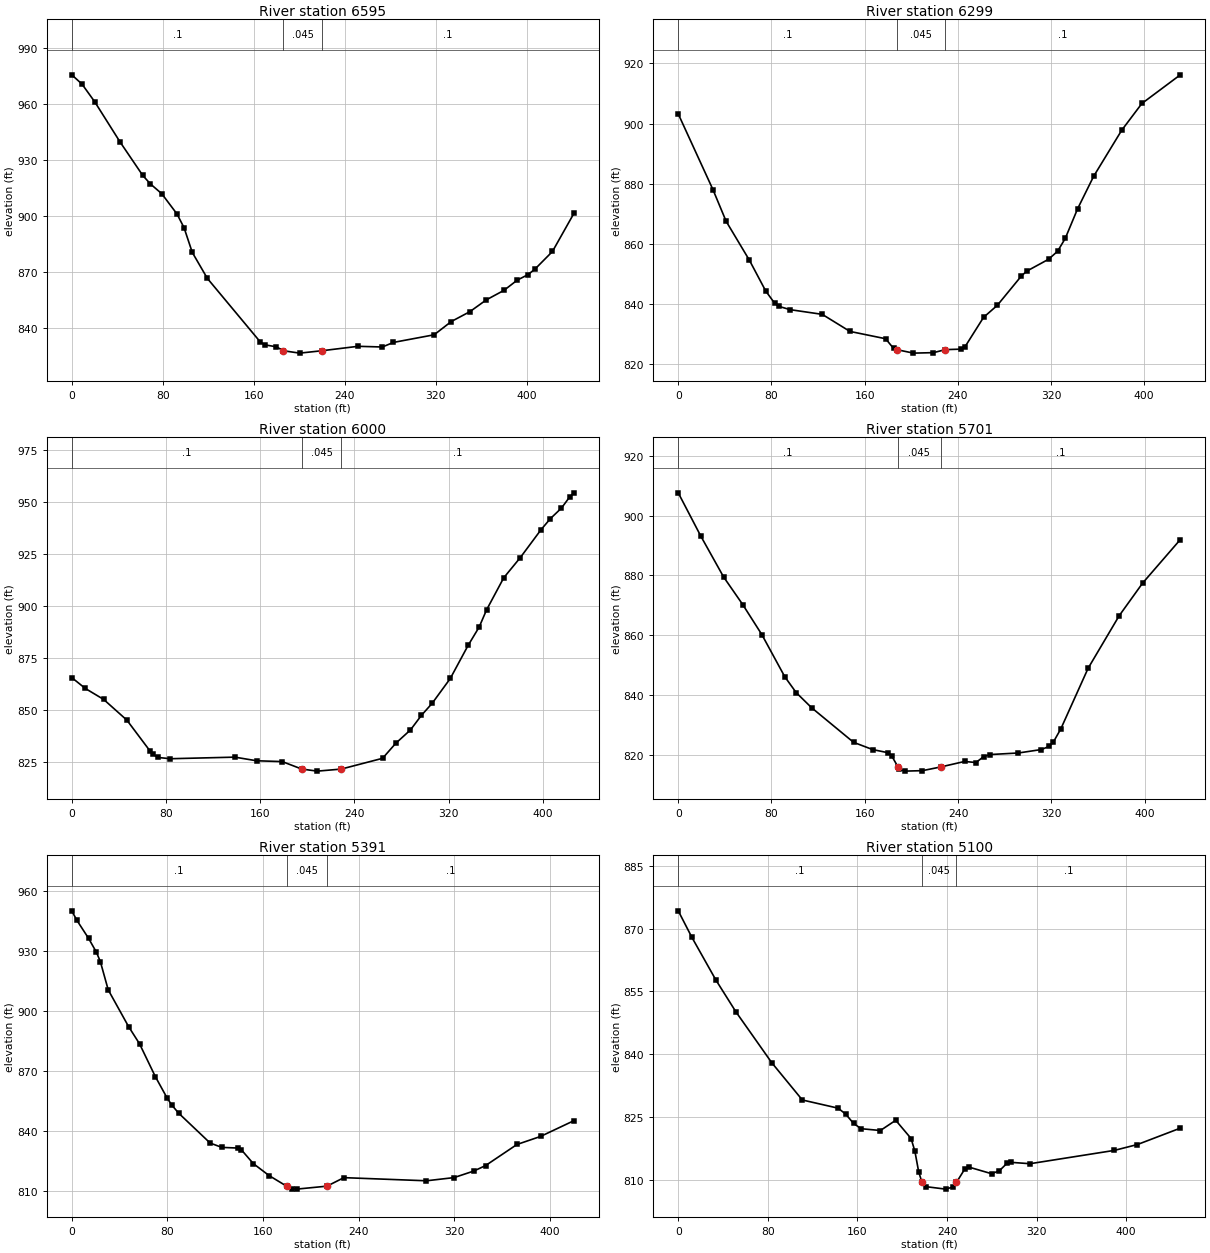
Type RM Length L Ch R = 1 ,6595    ,295.2,296.1,294.8
XS GIS Cut Line= 6
1649784.34170343467947.9308717551649767.88471533 468033.86902009
1649753.77877243468107.530618176  1649724.690576468205.544529751
1649683.10831009468277.2136777491649633.11694026468356.472705588
#Sta/Elev= 30
       0  975.46       9   970.5    20.2  961.03    42.4  939.62    62.4  921.69
    69.1  917.18    79.1  911.93    92.5  901.09    98.7  893.76   105.9  880.59
   119.2  866.66   165.7  832.72   169.5  831.19   179.8  830.14  186.07828.0157
   200.3  826.75  219.73828.0158   251.6  830.39     273  830.03   282.7  832.47
   318.5  836.55   333.6  843.64   349.9   848.9   364.4  855.22   379.9   860.3
   391.5  865.73   400.8  868.63     407  871.57   422.5  881.07   441.3  901.37
#Mann= 3, -1 ,  0
       0     0.1       0  186.07   0.045       0  219.73     0.1       0
Bank Sta=186.07,219.73
XS Rating Curve= 0 ,0
Exp/Cntr(USF)=0,0
Exp/Cntr=0.3,0.1

Type RM Length L Ch R = 1 ,6299    ,282.4,298.9,305.4
XS GIS Cut Line= 6
1649568.70302708467853.496677428 1649521.1854056467930.521129668
1649486.17628926467999.9576705841649457.45423384468095.978147835
1649434.42901742 468167.356285931649407.56653833468250.631053761
#Sta/Elev= 30
       0  903.21    29.8  878.07    41.1  867.56    61.1  854.62    75.1   844.4
    82.8  840.32    86.6  839.28    96.1   838.2   123.6  836.65   147.4  830.98
     178  828.55   184.8  825.36  187.48824.9383   201.9  823.77   219.1  823.93
   229.3  824.93     243   825.1   245.9  825.71   262.1  835.65   273.9  839.64
   294.6   849.4   299.1  850.98   317.9  854.94   325.6  857.58   332.2  861.84
   342.8  871.68   356.6  882.49   380.7  897.79     398  906.67     431  916.19
#Mann= 3, -1 ,  0
       0     0.1       0  187.48   0.045       0   229.3     0.1       0
Bank Sta=187.48,229.3
XS Rating Curve= 0 ,0
Exp/Cntr(USF)=0,0
Exp/Cntr=0.3,0.1

Type RM Length L Ch R = 1 ,6000    ,318.3,299.4,286.9
XS GIS Cut Line= 6
1649385.95568918467728.3604447541649326.70416726467794.263856262
1649272.49495809467846.3900643441649195.49248743467910.191774011
1649137.74063443467958.042728171 1649070.3634726468013.869060084
#Sta/Elev= 30
       0  865.39    11.5  860.16    27.1  854.87    46.8  844.91    66.6  829.95
      69  828.41    73.3  826.94    83.8  826.34   138.5   827.1   156.9  825.36
   178.7  824.96  195.34821.3569   208.5  820.37  228.78821.3552   263.9  826.54
   275.1  833.77   287.6  840.21   296.9  847.23     306  853.01   321.4  864.97
   336.5  880.86   345.9  889.71   352.2  897.99   366.8  913.45   380.8  923.12
   398.5  936.62   406.4  941.91   415.8  946.99   422.8  952.36   426.3  954.32
#Mann= 3, -1 ,  0
       0     0.1       0  195.34   0.045       0  228.78     0.1       0
Bank Sta=195.34,228.78
XS Rating Curve= 0 ,0
Exp/Cntr(USF)=0,0
Exp/Cntr=0.3,0.1

Type RM Length L Ch R = 1 ,5701    ,306.6,310,310.2
XS GIS Cut Line= 6
1648990.44335684467504.4780185071648990.44335684467591.977843508
1648990.44335684467666.9780215921648991.58902384467766.977821589
1648981.46273176467843.8428253381648962.61860934467932.543763429
#Sta/Elev= 30
       0   907.6    19.2  893.23    38.9  879.46    55.3  870.23    71.7  860.18
    91.4  846.06   101.2  840.75   114.4   835.7   150.4  824.12   166.8  821.69
     180  820.64   183.3  819.45  188.54815.8663   189.8  815.12   194.3  814.48
   209.5  814.64  225.05815.8641   245.6  817.71   255.4  817.36     262  819.33
   267.5  820.03   291.8  820.55   311.6  821.71   318.2  822.77   321.6  824.07
   328.2  828.62   351.6  848.89   378.3   866.5   398.4  877.41   430.7  891.96
#Mann= 3, -1 ,  0
       0     0.1       0  188.54   0.045       0  225.05     0.1       0
Bank Sta=188.54,225.05
XS Rating Curve= 0 ,0
Exp/Cntr(USF)=0,0
Exp/Cntr=0.3,0.1

Type RM Length L Ch R = 1 ,5391    ,296.1,290.6,284.4
XS GIS Cut Line= 4
 1648696.0639457467463.6722380641648696.31005741467607.457104184
1648678.16515551467810.9742000971648678.69732967 467883.00818589
#Sta/Elev= 30
       0   949.9     4.2  945.23    14.1  936.11    20.6  929.22    23.9  924.55
    30.5  910.38    47.5  892.07    56.7  883.43    69.9  867.05    79.7  856.42
    83.5  852.94    89.5  848.71   115.8   833.8   125.6  831.64   138.8  831.32
     142  830.38   151.9  823.54   165.1  817.56   179.7  812.28   184.1  811.02
   188.1  810.78  213.55812.2673   227.7  816.52   296.8  814.95   319.9  816.55
   336.4  819.83   346.2  822.54   372.5   833.1   392.2  837.11   420.1  844.98
#Mann= 3, -1 ,  0
       0     0.1       0   179.7   0.045       0  213.55     0.1       0
Bank Sta=179.7,213.55
XS Rating Curve= 0 ,0
Exp/Cntr(USF)=0,0
Exp/Cntr=0.3,0.1

Type RM Length L Ch R = 1 ,5100    ,271.7,311.7,327.5
XS GIS Cut Line= 6
1648415.94877093 467479.475443841648373.03809559467581.584819674
1648394.58923359467653.4216182531648423.32408425467749.204235092
1648444.87522225467821.041361749 1648470.0182166467904.851233512
#Sta/Elev= 30
       0  874.23    12.2  867.89    33.7  857.67    51.5  850.11    83.5  837.96
   110.8  829.06   142.8   827.1   149.6  825.66   156.5  823.47   163.3   822.2
   180.5  821.77   194.2  824.21   207.9  819.86   211.3  816.82   214.7  811.89
  217.65809.3769   221.5  808.35   238.7  807.77   245.6   808.3  248.43809.3767
   255.7  812.51   259.3  813.05   279.8  811.45   286.7  812.15   293.5  813.93
   296.9  814.17   314.1  813.84   389.4  817.02     410  818.42   448.3  822.33
#Mann= 3, -1 ,  0
       0     0.1       0  217.65   0.045       0  248.43     0.1       0
Bank Sta=217.65,248.43
XS Rating Curve= 0 ,0
Exp/Cntr(USF)=0,0
Exp/Cntr=0.3,0.1

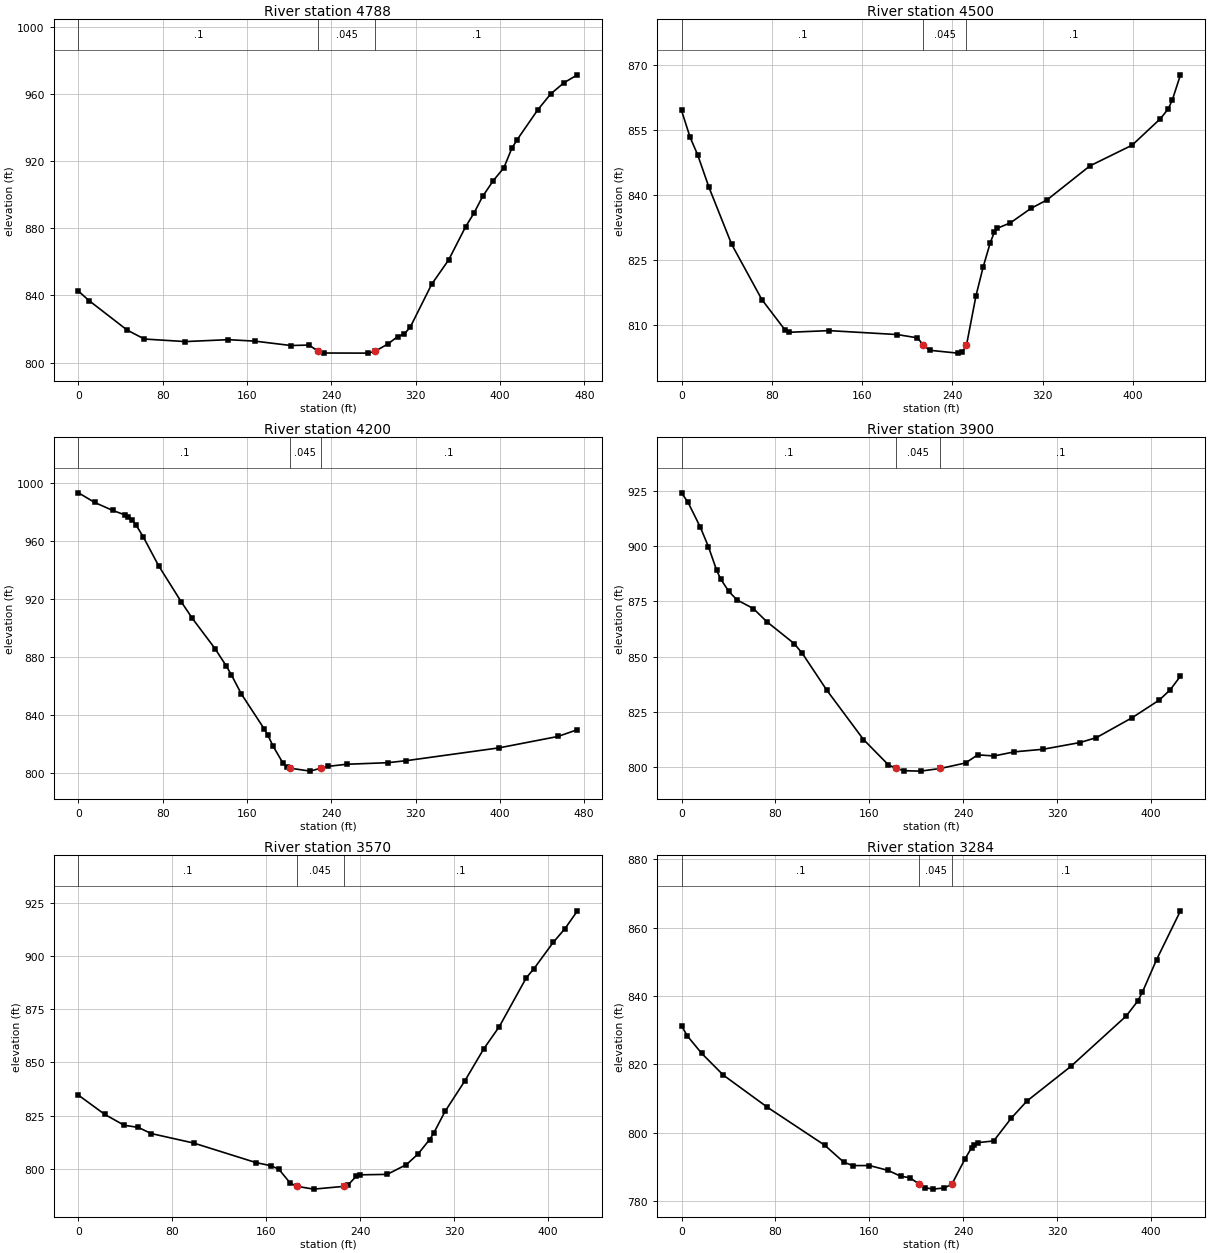
Type RM Length L Ch R = 1 ,4788    ,259.8,288.3,307.1
XS GIS Cut Line= 6
1648359.41287767467458.8962995061648261.96425367467553.413498918
1648203.94074767467601.2152405921648122.56722275467659.338812003
1648061.53683301467702.9315725961647990.33520376 467753.78973859
#Sta/Elev= 30
       0   842.5     9.9  836.93    46.2  819.32    62.5  813.99   101.4  812.47
     142  813.61   167.5  812.73   201.5  810.13   218.7  810.39  227.36 806.757
   232.5  805.66   274.8  805.59   281.6806.7682   293.6  811.07   302.8  815.42
     309  816.92   314.8   821.1   335.1  846.62   351.2  861.12   367.3  880.89
   375.4   889.2   383.4  898.92   393.6  908.38   403.6  916.01   411.2  927.71
   416.2  932.76   435.9  950.67     448  959.98   460.6  966.68   473.4   971.4
#Mann= 3, -1 ,  0
       0     0.1       0  227.36   0.045       0   281.6     0.1       0
Bank Sta=227.36,281.6
XS Rating Curve= 0 ,0
Exp/Cntr(USF)=0,0
Exp/Cntr=0.3,0.1

Type RM Length L Ch R = 1 ,4500    ,308.5,300,283.5
XS GIS Cut Line= 6
1648353.17541412467351.8790341591648275.89349138467367.174045276
1648175.90495968467379.2637020051648084.34083834467339.064963505
1648015.66709118467308.9160736651647935.54815692467273.742259502
#Sta/Elev= 30
       0  859.57     7.6  853.35    14.3  849.29    24.3  841.77    44.4  828.58
    71.2  815.77    91.8  808.71    94.8   808.2   130.7  808.59   191.1  807.68
     209  806.92   214.3805.2078   219.8  804.04   244.6  803.38   248.4  803.54
   252.4 805.156   260.9  816.71   267.2   823.3   273.5  828.93   277.1  831.38
   279.6  832.27   291.4  833.55   309.5  836.88   323.7  838.84   361.8  846.73
   399.2  851.53   424.2  857.65   431.2  859.93   434.8  862.01     442  867.81
#Mann= 3, -1 ,  0
       0     0.1       0   214.3   0.045       0   252.4     0.1       0
Bank Sta=214.3,252.4
XS Rating Curve= 0 ,0
Exp/Cntr(USF)=0,0
Exp/Cntr=0.3,0.1

Type RM Length L Ch R = 1 ,4200    ,311.4,300,286.1
XS GIS Cut Line= 6
1648408.84707908467002.2086818371648328.56115042467036.999622762
1648259.74468701467066.820429251  1648167.988965467106.581504583
1648081.58690684467139.1746152491647971.07991001 467183.01311025
#Sta/Elev= 30
       0  993.51    15.4  986.84    32.6   981.3    43.8  978.34    47.4   977.1
    50.9  975.04    54.5  971.47    61.7   962.8      76  943.21    97.4  918.36
   108.1  906.72   129.6  885.86   140.2  873.96   145.2  867.66   154.6  854.52
   176.1  830.58   179.7  826.13   184.8  818.35     194  806.89   197.6  803.97
  200.92803.2027     220  801.16  229.99 803.202   236.9  804.45   254.7  805.91
   293.5  806.98     311  808.36   399.6  817.28   455.2  825.12   473.7  829.81
#Mann= 3, -1 ,  0
       0     0.1       0  200.92   0.045       0  229.99     0.1       0
Bank Sta=200.92,229.99
XS Rating Curve= 0 ,0
Exp/Cntr(USF)=0,0
Exp/Cntr=0.3,0.1

Type RM Length L Ch R = 1 ,3900    ,337.2,330.1,327.7
XS GIS Cut Line= 6
1648032.88195176466744.1744210121648004.01193076466826.774649501
1647979.26624534466897.5747047511647946.27188876466991.974778429
1647921.52620333467062.7748336791647891.04955825467144.813383505
#Sta/Elev= 30
       0  924.07     5.6  919.71      16  908.56    22.9  899.75    29.9  889.08
    33.4  885.07    40.3  879.47    47.3  875.66    61.2  871.74    72.7  865.79
    95.9  855.94   102.9  851.49   123.7  834.89     155  812.55     176  801.21
  182.64799.4675   189.8  798.44   203.7  798.26  220.52799.4668   241.9  801.94
   252.3  805.62   266.2  805.12   283.6  806.98   307.9  808.14   339.2  811.16
   353.3  813.38   383.9  822.43   406.9  830.37   416.2  834.98     425  841.21
#Mann= 3, -1 ,  0
       0     0.1       0  182.64   0.045       0  220.52     0.1       0
Bank Sta=182.64,220.52
XS Rating Curve= 0 ,0
Exp/Cntr(USF)=0,0
Exp/Cntr=0.3,0.1

Type RM Length L Ch R = 1 ,3570    ,274.9,285.4,292.4
XS GIS Cut Line= 6
1647666.78171701466641.8203921321647658.91887184466728.966215209
1647652.17905593466803.6629162141647643.19285343 466903.25818947
1647636.45303752 466977.954890461647628.58986426467065.100713551
#Sta/Elev= 30
       0  834.59    22.4  825.54    38.9  820.43    50.9  819.43    61.9  816.53
    98.2  812.04   150.9  802.89     164  801.35   170.6  799.76   180.5   793.1
  186.22 791.655   200.3  790.35  225.92791.6403   229.9  792.51   236.5  796.34
   239.8  797.08   262.9   797.3   279.3  801.88   289.2  806.89   299.1   813.7
   302.4  816.56   312.3  827.01   328.9  841.16   345.2  856.42   358.4  866.84
   381.4  889.86     388   894.2   404.4  906.57   414.4  913.05     425  921.42
#Mann= 3, -1 ,  0
       0     0.1       0  186.22   0.045       0  225.92     0.1       0
Bank Sta=186.22,225.92
XS Rating Curve= 0 ,0
Exp/Cntr(USF)=0,0
Exp/Cntr=0.3,0.1

Type RM Length L Ch R = 1 ,3284    ,285.4,284.6,281.5
XS GIS Cut Line= 6
1647508.56984956 466584.551467141647457.77205088466655.797059555
1647414.05396246466716.7372263861647355.76274047466797.991000895
1647312.04498013466858.9314958051647261.03983281466930.028138388
#Sta/Elev= 30
       0  831.25     4.9   828.3    17.1   823.2    35.5  816.84    73.1  807.42
     122  796.29   138.1  791.36   145.8  790.33   160.1  790.35   175.9  788.94
   186.6  787.23   194.6  786.78   202.5784.8911   207.1   783.9   214.2  783.45
   223.6  783.79   230.2  784.83   241.4  792.23   247.1   795.6   249.5  796.43
   252.7  797.06   265.9  797.55   280.8  804.18   294.1  809.19   331.8  819.41
   378.8  834.11   388.5  838.43   392.5  841.02   404.6  850.56     425  864.88
#Mann= 3, -1 ,  0
       0     0.1       0   202.5   0.045       0   230.2     0.1       0
Bank Sta=202.5,230.2
XS Rating Curve= 0 ,0
Exp/Cntr(USF)=0,0
Exp/Cntr=0.3,0.1

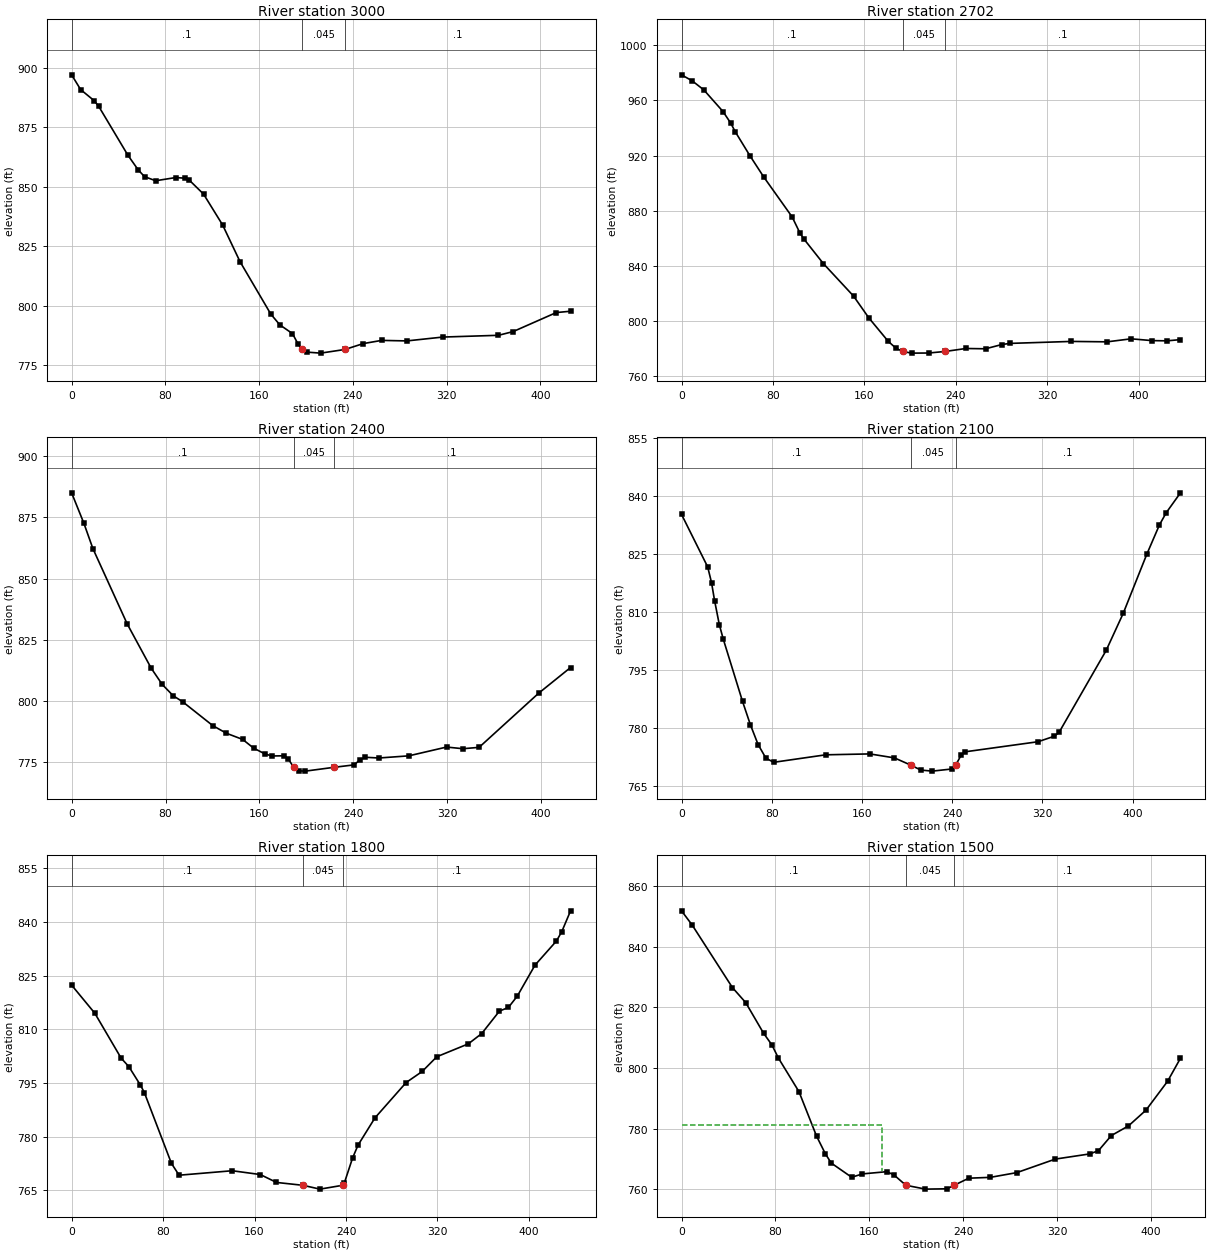
Type RM Length L Ch R = 1 ,3000    ,311.6,297.5,281.4
XS GIS Cut Line= 6
1647286.38016392466391.7975010871647240.23393075466466.093612343
1647200.67561093466529.782133251   1647147.61699466614.563131675
1647108.25814484466678.462938249  1647055.656544466749.337468416
#Sta/Elev= 30
       0   897.1     7.7   890.9    19.3  886.22    23.2   883.8    47.9  863.43
    56.7  857.25    62.2  854.33    71.7   852.6    88.8  853.94    96.6  853.69
   100.4  852.86   112.6  846.99   128.9     834   143.7  818.63     170  796.57
   177.7  792.05   188.5  788.38   193.2  784.04  196.73781.7123   200.9   780.6
   212.5  780.18  233.26781.7156   248.9  784.19   264.6  785.53     286  785.31
   316.8  786.93   364.3  787.67   376.8  789.23   413.6  797.22   425.8  797.78
#Mann= 3, -1 ,  0
       0     0.1       0  196.73   0.045       0  233.26     0.1       0
Bank Sta=196.73,233.26
XS Rating Curve= 0 ,0
Exp/Cntr(USF)=0,0
Exp/Cntr=0.3,0.1

Type RM Length L Ch R = 1 ,2702    ,311.2,302.3,292.3
XS GIS Cut Line= 6
1646845.46437909466310.4354590921646864.26453835466395.891981095
1646880.37900743466469.1401941781646906.32810251466565.823071674
1646937.04523267 466635.858692751646969.59503634466727.783705756
#Sta/Elev= 30
       0   978.5     9.4  974.11    19.5   967.6    36.3  951.91      43  943.59
      47   937.3    59.8  919.97    71.8  904.68    96.8  875.55   103.5   864.1
   106.8  859.86   124.1  841.77   150.5  818.24     164  802.31   180.9  785.41
   187.7   780.4  193.66778.0635   201.3  776.88   216.2  776.96  230.47778.0645
   248.9  780.24     266  780.02   280.4  783.13   287.5  783.93   341.2  785.36
   372.4  785.06   393.4  787.25   411.5  785.96   424.7  785.78   436.6  786.66
#Mann= 3, -1 ,  0
       0     0.1       0  193.66   0.045       0  230.47     0.1       0
Bank Sta=193.66,230.47
XS Rating Curve= 0 ,0
Exp/Cntr(USF)=0,0
Exp/Cntr=0.3,0.1

Type RM Length L Ch R = 1 ,2400    ,301.6,300,299.2
XS GIS Cut Line= 6
  1646529.712714466574.6127522591646591.18929709466636.877391502
1646643.88341743466690.2470354291646714.14213517466761.406670004
1646766.83625551 466814.776642011646828.31251051466877.041281253
#Sta/Elev= 30
       0  885.03    10.5  872.54    18.1  862.29    47.4  831.45    67.8  813.41
    77.2  806.77    86.5  802.19    94.7  799.67   120.2  789.99   131.8  786.86
   145.7  784.33     155   780.8   164.3   778.5   170.5  777.57   181.1  777.66
   184.6  776.33  189.22772.9297   193.9  771.48   199.1  771.39  223.18772.9277
   240.6  773.94   245.7  776.05   250.1  777.05   261.7  776.75   287.2  777.63
   319.4  781.22   333.3  780.54   347.1   781.1   397.8   803.2     425   813.7
#Mann= 3, -1 ,  0
       0     0.1       0  189.22   0.045       0  223.18     0.1       0
Bank Sta=189.22,223.18
XS Rating Curve= 0 ,0
Exp/Cntr(USF)=0,0
Exp/Cntr=0.3,0.1

Type RM Length L Ch R = 1 ,2100    ,263.7,300,317.9
XS GIS Cut Line= 6
 1646372.4712306466769.9443825931646403.60568276466869.313934505
1646453.37362784 466926.480486841646529.24093017 466991.62766625
1646586.14140692467040.4878047561646652.52546051467097.491627753
#Sta/Elev= 30
       0  835.13    23.2  821.55    26.6  817.49    29.3  812.86    33.5  806.64
    36.9  802.99    54.1  786.77      61   780.8    67.9  775.62    74.8  772.12
    81.7  771.03   127.9  772.97     167   773.2   188.8  772.17  203.61770.2621
   212.1  769.03   222.3  768.75   239.6   769.3  243.06770.2615   248.2  773.04
   251.6  773.75   316.1  776.35   330.4  777.76   334.7  778.74   376.5  799.95
   391.6  809.52   412.5  824.79   423.8  832.44   429.8  835.57   442.4   840.7
#Mann= 3, -1 ,  0
       0     0.1       0  203.61   0.045       0  243.06     0.1       0
Bank Sta=203.61,243.06
XS Rating Curve= 0 ,0
Exp/Cntr(USF)=0,0
Exp/Cntr=0.3,0.1

Type RM Length L Ch R = 1 ,1800    ,288.4,300,308.7
XS GIS Cut Line= 6
1646317.21117051 466766.480150671646293.08490643466862.385470673
1646251.62731217466924.9017498341646197.93975551467009.267722845
  1646157.674088467072.5425306711646110.69747593467146.362921089
#Sta/Elev= 30
       0  822.36    20.3  814.49    43.3  801.95    50.1  799.55    60.2   794.4
    63.6  792.33    87.3  772.53      94  769.22   140.5  770.47     165  769.41
   179.2   767.2   202.4766.3957   217.2  765.33  236.97766.3953   238.6  767.12
   245.7     774   250.5  777.62   265.3  785.24   292.6  795.13   306.6  798.21
   319.4  802.33     347  805.94   358.7  808.82   374.2   815.1     382   816.1
   389.8  819.28   405.3  827.94     424  834.67   428.7  837.29   436.4  843.12
#Mann= 3, -1 ,  0
       0     0.1       0   202.4   0.045       0  236.97     0.1       0
Bank Sta=202.4,236.97
XS Rating Curve= 0 ,0
Exp/Cntr(USF)=0,0
Exp/Cntr=0.3,0.1

Type RM Length L Ch R = 1 ,1500    ,290.4,300,310.9
XS GIS Cut Line= 6
1646207.89216343466645.4128075091646132.21908642466689.622692838
1646066.50629134466725.8509668411645977.44282117466771.323316842
1645910.64538258 466805.427251251645832.71476418466845.215557501
#Sta/Elev= 30
       0  851.93     9.1  847.23    43.4  826.57    54.7  821.62    69.9  811.51
      77  807.66    82.6  803.28   100.1  792.19   115.1   777.5   122.6  771.67
   127.6  768.62     145  763.93   154.2  765.04   174.8  765.77   180.9  764.75
   191.2761.2845   207.9  760.01   226.4  760.12  232.37761.2853   244.8  763.62
   263.2   763.9   285.8  765.47   318.5  769.93   347.9  771.64   355.3  772.71
   366.3  777.71   380.9   780.9   395.8  786.09   414.2  795.62   425.2  803.25
#Mann= 3, -1 ,  0
       0     0.1       0   191.2   0.045       0  232.37     0.1       0
#XS Ineff= 2 , 0
          170.44  781.32
Permanent Ineff=
       F       F
Bank Sta=191.2,232.37
XS Rating Curve= 0 ,0
Exp/Cntr(USF)=0,0
Exp/Cntr=0.3,0.1