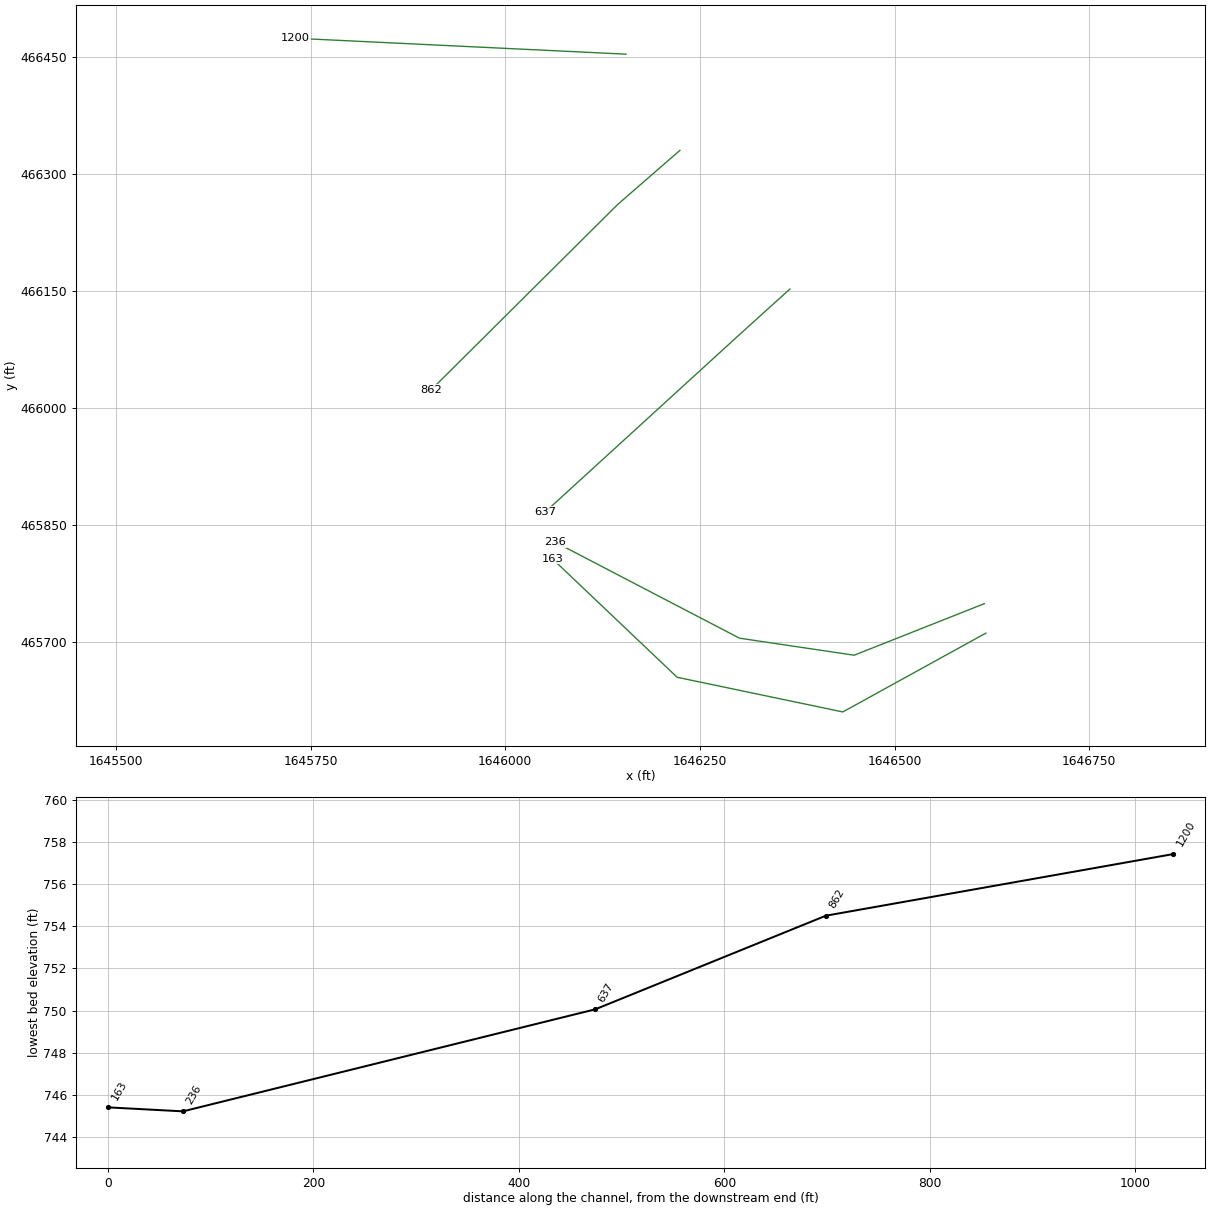
HEC-RAS study MagtyRn.prj: MagtyRn

--- MagtyRn.g01 (geometry) --- (continued)

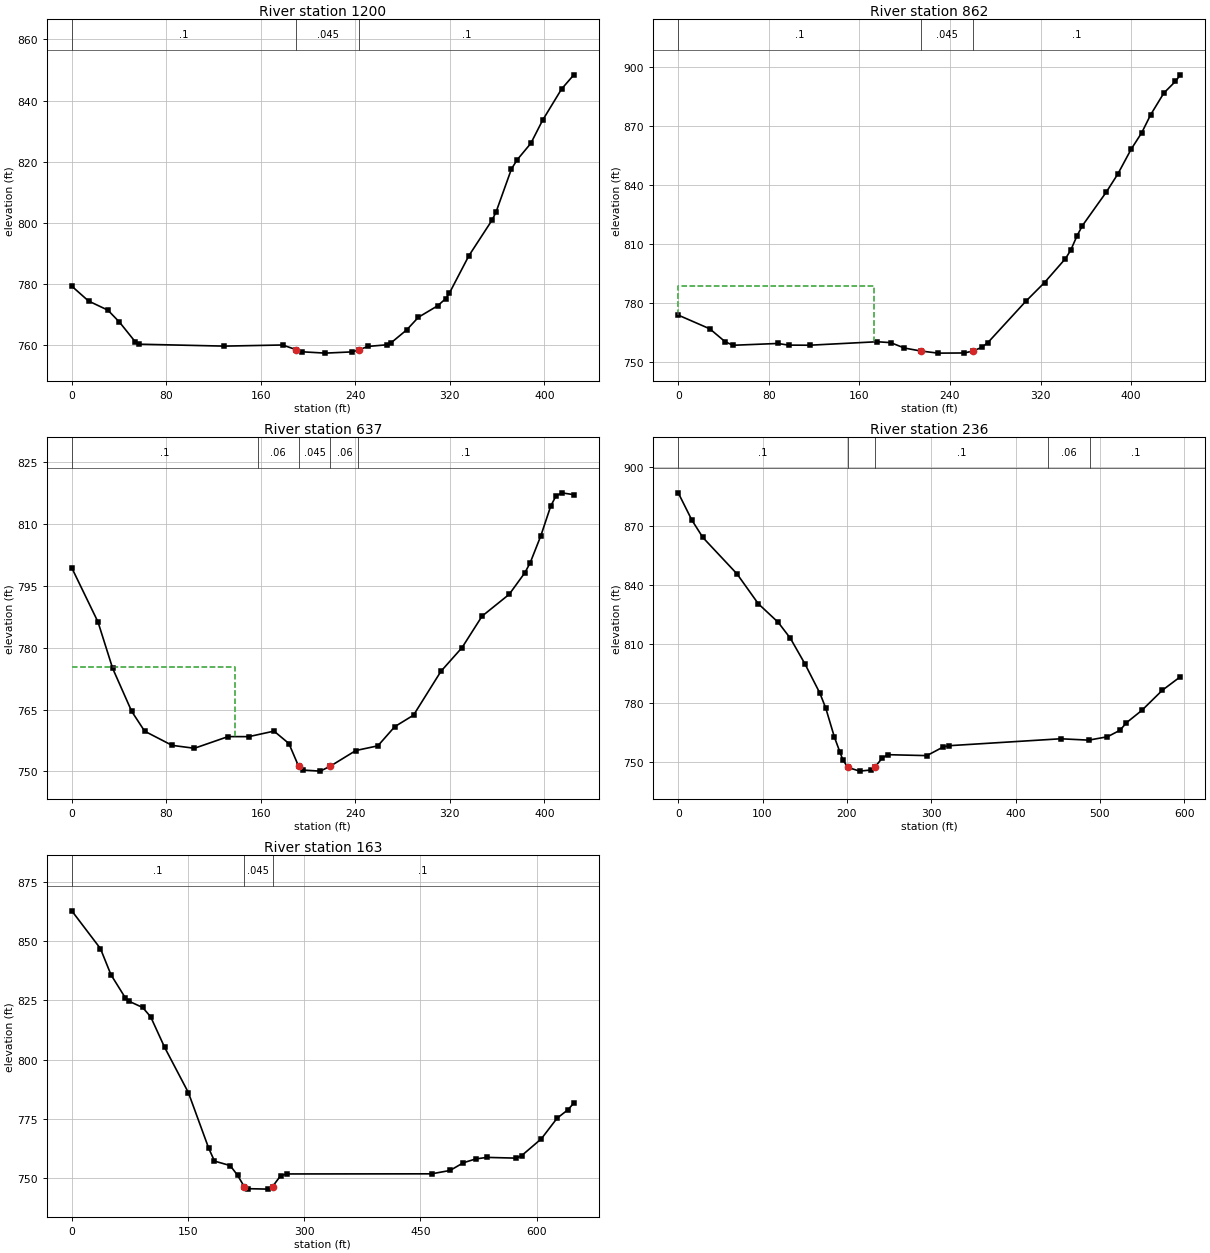
Type RM Length L Ch R = 1 ,1200    ,316.1,338.3,357.2
XS GIS Cut Line= 6
1646155.16753134466454.0634526761646067.76842792466458.265544012
1645992.85519193466461.8672428431645892.97054918466466.669070512
 1645818.0569851466470.2710974221645730.65788168466474.472860679
#Sta/Elev= 30
       0  779.33    14.2  774.47    30.6  771.48    40.4  767.56    53.6  761.21
    56.9  760.36   129.1  759.73   178.4   760.1  189.98758.5692   194.8  757.88
   214.5  757.44   237.5  757.85  243.51758.5699   250.7  759.63   266.7  760.16
   270.4  760.85   283.5  765.03   293.4  769.16   309.8  772.93   316.4   775.2
   319.6  777.01   336.1  789.24   355.8  800.93   359.1   803.5   372.2  817.65
   377.1  820.67   388.6  826.01   398.5  833.52   414.7  843.81     425   848.4
#Mann= 3, -1 ,  0
       0     0.1       0  189.98   0.045       0  243.51     0.1       0
Bank Sta=189.98,243.51
XS Rating Curve= 0 ,0
Exp/Cntr(USF)=0,0
Exp/Cntr=0.3,0.1

Type RM Length L Ch R = 1 ,862     ,225.2,224.5,224.6
XS GIS Cut Line= 6
1646224.41419252466330.6128079491646144.47950726 466261.15755918
1646091.26603102466208.3056307671646020.31538552466137.835955435
1645967.10223736 466084.983370851645905.02034051 466023.32240493
#Sta/Elev= 30
       0  773.85    27.9  766.86    41.3  760.36    48.3   758.5    87.8  759.42
    97.4  758.59     116  758.53   175.5   760.3   187.6  759.85   199.8  757.09
  214.28755.5842   229.4  754.51   252.6  754.59  260.18 755.566     268  757.43
   273.5  759.89   306.9  780.84   323.5  790.41     342  802.59   346.6  806.82
   352.3  814.31     357  819.39   377.9  836.29   388.2  845.58     400  858.23
   409.3  866.56   417.3  875.83   428.9   886.8   439.1   892.7   443.4  896.03
#Mann= 3, -1 ,  0
       0     0.1       0  214.28   0.045       0  260.18     0.1       0
#XS Ineff= 2 , 0
           172.7  788.53
Permanent Ineff=
       F       F
Bank Sta=214.28,260.18
XS Rating Curve= 0 ,0
Exp/Cntr(USF)=0,0
Exp/Cntr=0.3,0.1

Type RM Length L Ch R = 1 ,637     ,415.8,401.3,388.5
XS GIS Cut Line= 6
1646365.66554302466152.5649809131646300.71947869466093.926318664
1646245.31801469466043.3729420941646171.44939602465975.967565093
1646116.04793202465925.4138604141646051.41321876465866.434647668
#Sta/Elev= 30
       0  799.35    22.2  786.22    34.6  774.98    50.7  764.56    61.7  759.74
    84.9  756.31   103.8   755.6   132.3  758.43   149.9  758.42   171.2  759.76
   183.8  756.75  191.94751.2844   195.6  750.32   210.4  750.06     219751.2844
   240.5  755.06   259.1  756.19   273.4  760.84   289.3  763.63   312.5  774.26
   330.4  780.02   347.3  787.63   370.3  792.93   383.6  798.18   388.1  800.61
     397  807.07   405.4  814.28   409.7  816.69   414.7  817.53     425  817.08
#Mann= 5, -1 ,  0
       0     0.1       0   157.5    0.06       0  191.94   0.045       0
     219    0.06       0   242.5     0.1       0
#XS Ineff= 2 , 0
          137.93  775.23
Permanent Ineff=
       F       F
Bank Sta=191.94,219
XS Rating Curve= 0 ,0
Exp/Cntr(USF)=0,0
Exp/Cntr=0.3,0.1

Type RM Length L Ch R = 1 ,236     ,73.6,73.1,71.3
XS GIS Cut Line= 4
1646615.33914089465748.6997495121646448.18394337465682.549924873
1646300.91544767 465704.397448961646064.35919505465827.563655847
#Sta/Elev= 30
       0  886.64    16.1  872.82    29.2  863.94    69.7  845.43    94.9  830.29
   118.5  820.83   132.9  812.76   150.2  799.73   167.9  784.87   174.9  777.24
   185.2  762.45   191.8  754.78   195.1  751.05  200.93747.1411     215  745.21
   228.3  745.78  232.96747.1383   241.5  751.65   248.2  753.57   294.8  753.09
   314.5  757.57   321.1  758.13   453.4  761.65   486.7  760.96   508.9  762.67
   523.9     766   531.3  769.77   549.6  776.05   573.9  786.28   595.3  793.15
#Mann= 5, -1 ,  0
       0     0.1       0  200.93   0.045       0  232.96     0.1       0
  438.65    0.06       0  488.65     0.1       0
Bank Sta=200.93,232.96
XS Rating Curve= 0 ,0
Exp/Cntr(USF)=0,0
Exp/Cntr=0.3,0.1

Type RM Length L Ch R = 1 ,163     ,,,
XS GIS Cut Line= 4
1646617.29996315 465710.870789431646433.61892731465609.724844584
1646220.80785935465654.2290603161646060.59268271465806.352561365
#Sta/Elev= 30
       0  862.76      37  846.83    50.6   835.8    69.1  826.08      74  824.61
    91.5     822   101.8  818.08   119.8  805.22   150.5   786.1   176.7  762.67
   184.2  757.22   204.4  755.34     214  751.24  222.49 746.505   227.1  745.59
   253.9   745.4  259.19746.5058   269.5  751.04   277.4   751.8   464.4  751.85
   488.2  753.27   505.5  756.54   521.5  758.14   535.8  758.78   573.9  758.47
   580.6  759.52   606.1  766.64   626.4  775.32   640.7  778.94     648  781.76
#Mann= 3, -1 ,  0
       0     0.1       0  222.49   0.045       0  259.19     0.1       0
Bank Sta=222.49,259.19
XS Rating Curve= 0 ,0
Exp/Cntr(USF)=0,0
Exp/Cntr=0.3,0.1
LCMann Table=0

Chan Stop Cuts=-1
Use User Specified Reach Order=0
Composite Channel Slope=5